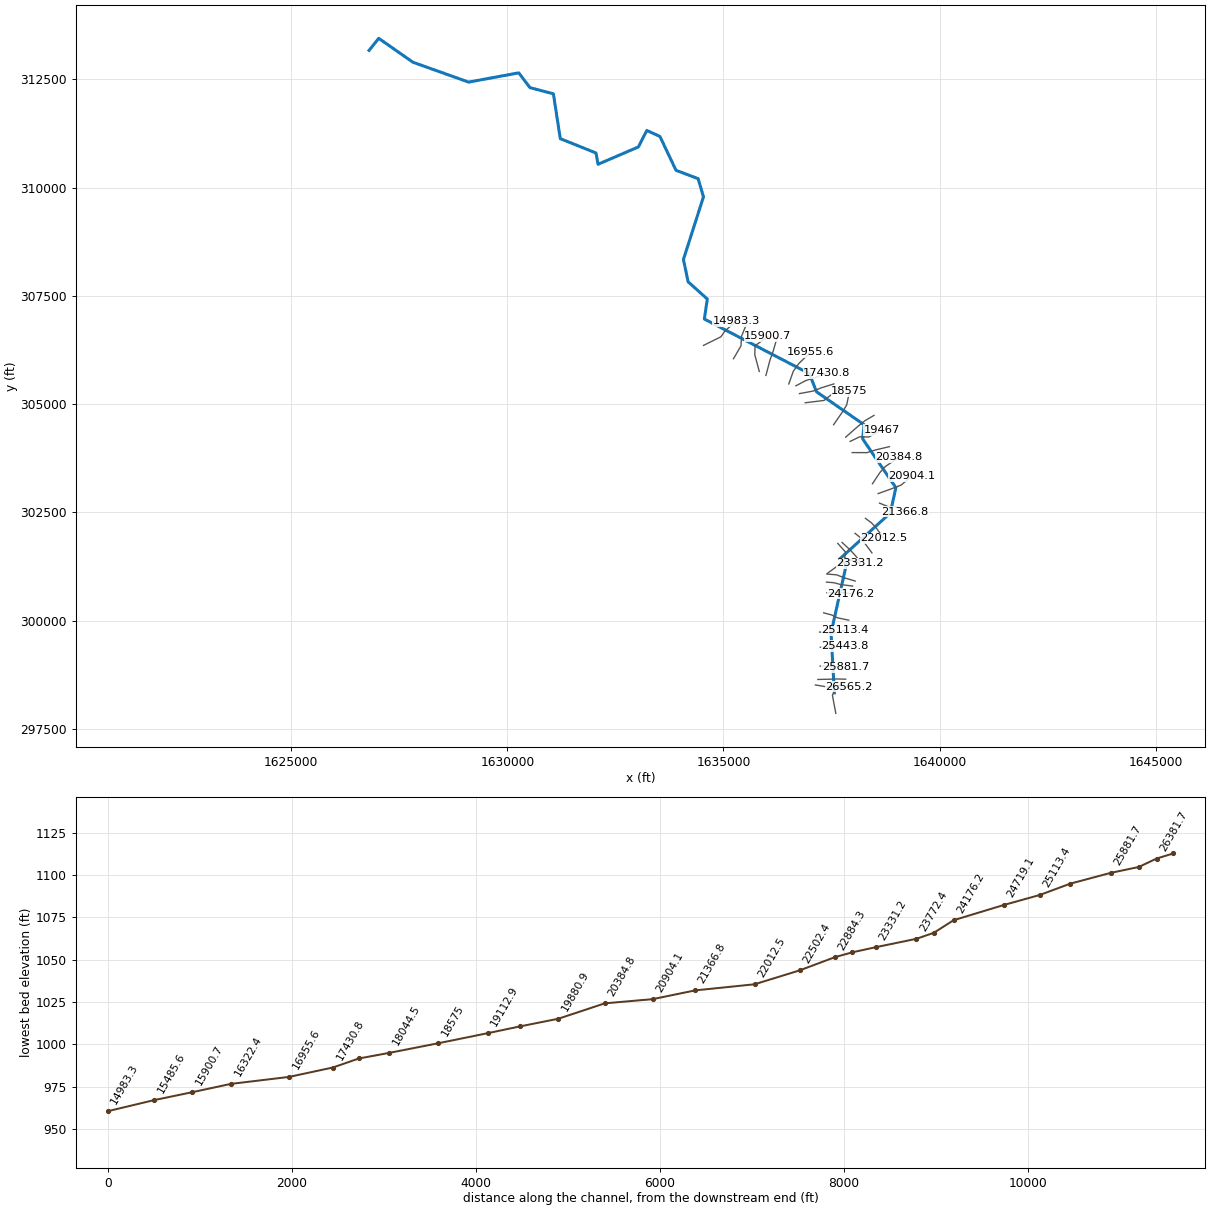
--- lrlfrk.prj (project) ---

Proj Title=lrlfrk
Current Plan=p01
Default Exp/Contr=0,0
English Units
Geom File=g01
Flow File=f01
Plan File=p01
BEGIN DESCRIPTION:
END DESCRIPTION:
DSS Export Rating Curves= 0
DSS Export Rating Curve Sorted= 0
DSS Export Volume Flow Curves= 0
DXF OffsetX= 0
DXF OffsetY= 0
DXF ScaleX= 0
DXF ScaleY= 0

--- lrlfrk.p01 (plan) ---

Plan Title=Floodplain
Program Version=4.00
Geom File=g01
Flow File=f01
K Sum by GR=0
Std Step Tol=0.01
Critical Tol=0.01
Num of Std Step Trials=20
Max Error Tol=0.3
Flow Tol Ratio=0.001
Split Flow NTrial=30
Split Flow Tol=0.02
Split Flow Ratio=0.02
Log Output Level=0
Friction Slope Method=1
Unsteady Friction Slope Method=2
Unsteady Bridges Friction Slope Method=1
Global Log Level=0
CheckData=False
Run HTab=0
Run UNet=0
Run PostProcess=0
UNET Theta=0
UNET Theta Warmup=0
UNET ZTol=0
UNET ZSATol=0
UNET MxIter=0
UNET MaxInSteps=0
UNET DtIC=0
UNET DtMin=0
UNET MaxCRTS=0
UNET WFStab=0
UNET SFStab=0
UNET WFX=0
UNET SFX=0
UNET DSS MLevel=0
UNET DZMax Abort=0
UNET Convert EG Bridges=0
UNET Use Existing IB Tables=0
UNET Froude Limit=0
UNET Froude Power=0
Write IC File=0
Echo Input=False
Echo Output=False
Write Detailed=0

--- lrlfrk.f01 (steady flow) ---

Flow Title=NFF Regression Equation
Program Version=4.00
Number of Profiles= 1
Profile Names=P100yr
River Rch & RM=lrlfrk,Main            ,26565.2
     309
River Rch & RM=lrlfrk,Main            ,26381.7
     311
River Rch & RM=lrlfrk,Main            ,26189.3
     379
River Rch & RM=lrlfrk,Main            ,25881.7
     384
River Rch & RM=lrlfrk,Main            ,23075.7
     422
River Rch & RM=lrlfrk,Main            ,22884.3
     474
River Rch & RM=lrlfrk,Main            ,20904.1
     503
River Rch & RM=lrlfrk,Main            ,20384.8
     573
River Rch & RM=lrlfrk,Main            ,19880.9
     611
River Rch & RM=lrlfrk,Main            ,17713.8
     657
River Rch & RM=lrlfrk,Main            ,14393.1
     725
River Rch & RM=lrlfrk,Main            ,14030.2
     931
River Rch & RM=lrlfrk,Main            ,13537.7
     977
River Rch & RM=lrlfrk,Main            ,9106.5
    1071
River Rch & RM=lrlfrk,Main            ,6409.1
    1155
River Rch & RM=lrlfrk,Main            ,727.8
    1282
Boundary for River Rch & Prof#=lrlfrk,Main            , 1
Up Type= 0
Dn Type= 1
Dn Known WS=856.3
DSS Import GetInterval= 0
DSS Import GetPeak= 0
DSS Import FillOption= 0

--- lrlfrk.g01 (geometry) ---

Geom Title=USGS 10m DEM
Program Version=4.00

River Reach=lrlfrk          ,Main
Reach XY= 30
     1637565.164      298333.301     1637487.576       299713.22
     1637841.603      301294.778      1637693.19      301427.848
      1638860.26      302485.506     1638987.151      303069.565
     1638219.714       304195.63     1638253.665      304522.116
     1637151.774      305283.313     1636985.667      305702.748
     1634557.636      306962.722     1634625.476      307425.405
     1634182.216      307822.188     1634073.155      308338.603
     1634536.834      309784.447     1634413.238      310203.786
     1633901.611      310396.869     1633529.223      311179.572
     1633225.536      311316.396     1633031.651      310936.856
     1632097.571      310535.965     1632050.701       310796.92
     1631224.524      311127.451     1631065.228      312163.321
     1630523.023      312305.597     1630263.725      312647.075
     1629104.286       312433.44     1627815.914      312891.917
     1627024.379      313443.962     1626801.239      313165.844

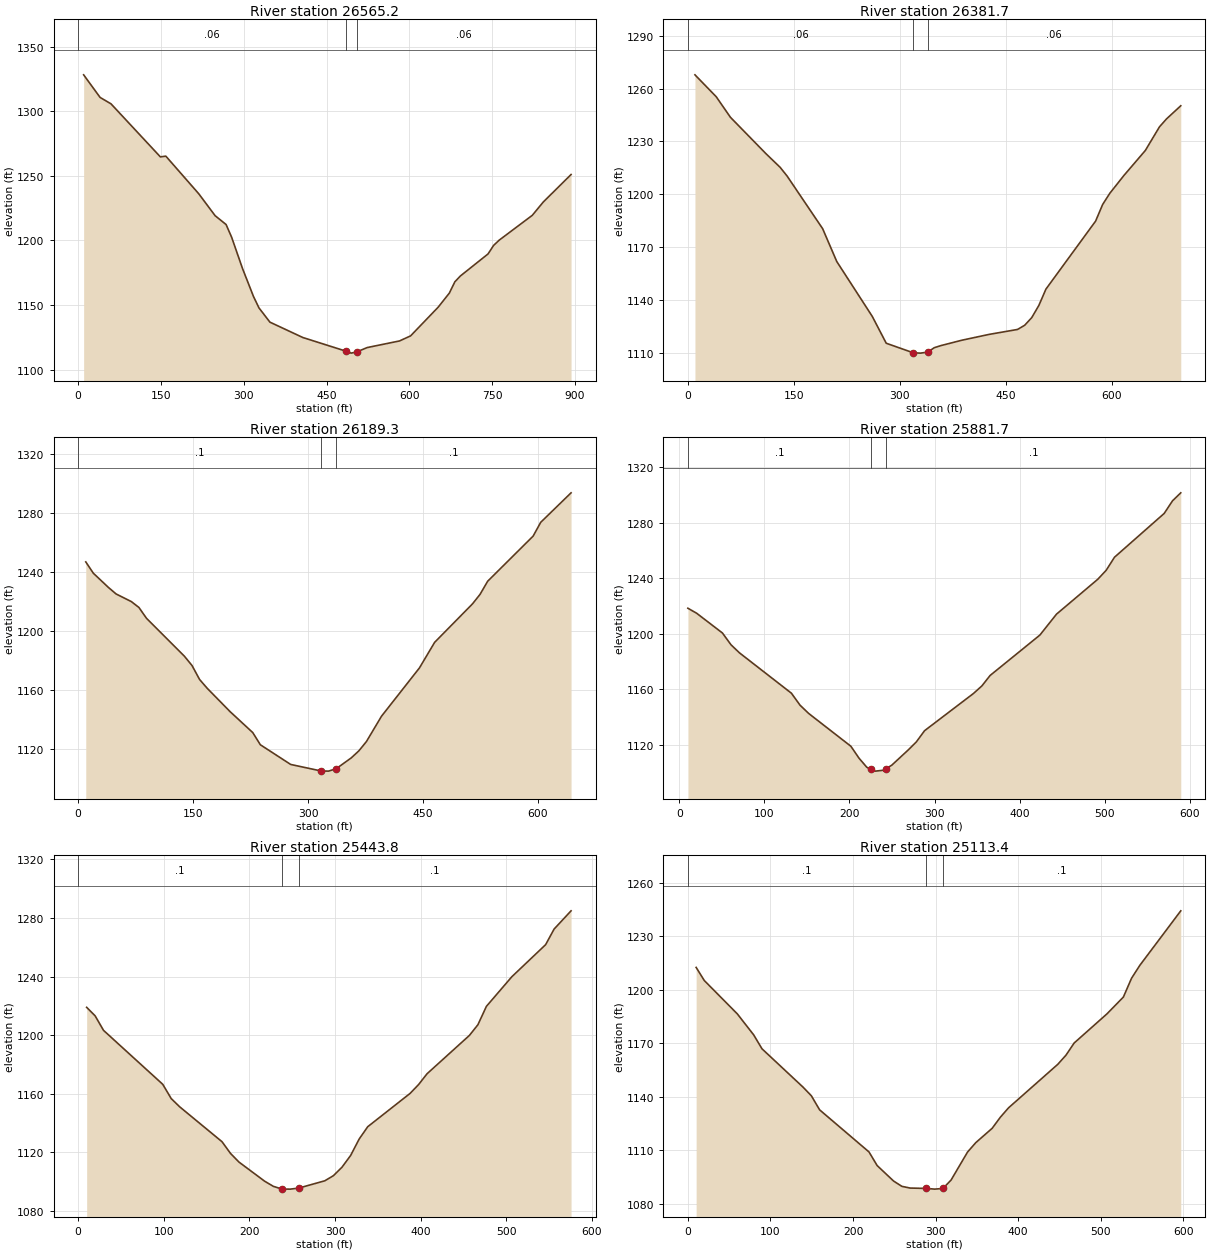
Type RM Length L Ch R = 1 ,26565.2 ,205.7,183.5,161.2
XS GIS Cut Line= 4
     1637597.953      297858.398     1637519.392      298277.834
     1637585.969      298406.994     1637898.882      298477.566
#Sta/Elev= 30
     9.9 1328.33    39.7 1310.82    59.5 1305.84   148.9 1264.76   158.8 1265.33
   218.3 1236.25   248.1  1219.2   267.9 1212.37   277.9 1202.61   297.7 1178.25
   317.6 1156.57   327.5 1147.77   347.3 1136.75   406.9 1124.85   484.5 1114.34
   494.5 1112.75   504.5  1113.7   523.6 1117.07   582.1 1122.19   602.1  1126.1
   652.2 1148.39   672.3 1159.24   682.3    1168   692.3 1172.51   742.4 1189.58
   752.5  1196.2   762.5 1200.22   822.6 1219.51   842.7 1229.92   892.8  1251.1
#Mann= 3 , 0 , 0
       0     .06       0   484.5    .045       0   504.5     .06       0
Bank Sta=484.5,504.5
XS Rating Curve= 0 ,0
Exp/Cntr=0.3,0.1

Type RM Length L Ch R = 1 ,26381.7 ,191.5,192.4,193.3
XS GIS Cut Line= 4
     1637126.259      298514.798     1637393.427      298469.615
      1637548.83      298469.367     1637807.931      298549.176
#Sta/Elev= 30
      10  1267.8    40.1 1255.36    60.2 1243.68   110.4 1223.04   130.5 1215.28
   140.5 1210.25   190.7  1180.4   210.7 1161.74   260.9  1130.6   280.7 1115.32
   319.2 1109.87   329.2 1109.71   339.2 1110.27   348.7  1112.8   358.4 1114.02
   387.5 1117.02   426.4 1120.36   466.5 1123.16   476.6 1125.53   486.6 1129.88
   496.7 1136.83   506.7 1146.08     577 1184.71     587 1194.18   597.1 1200.51
   617.1 1210.65   647.3  1224.8   667.4 1238.27   677.4 1242.79   697.5 1250.22
#Mann= 3 , 0 , 0
       0     .06       0   319.2    .045       0   339.2     .06       0
Bank Sta=319.2,339.2
XS Rating Curve= 0 ,0
Exp/Cntr=0.3,0.1

Type RM Length L Ch R = 1 ,26189.3 ,309.2,307.6,306
XS GIS Cut Line= 4
     1637182.511      298641.346     1637430.178      298646.672
     1637617.926       298653.33     1637825.647      298648.004
#Sta/Elev= 30
     9.9  1246.9    19.8  1239.2    39.6 1229.49    49.5 1225.11    69.4 1219.93
    79.3 1215.93    89.2 1208.56   138.7 1182.79   148.6  1176.5   158.5 1166.99
   168.5 1160.99   198.2 1145.22   227.9 1130.92   237.8 1122.66   277.4 1109.27
   316.8 1104.88   326.8 1104.74   336.8 1106.37   356.5 1113.75   366.4 1118.51
   376.3 1124.86     396 1142.08   445.5 1174.88   465.3 1192.23   514.7 1218.37
   524.6 1224.85   534.5 1233.73   593.9 1264.44   603.8  1273.8   643.4 1293.83
#Mann= 3 , 0 , 0
       0      .1       0   316.8    .045       0   336.8      .1       0
Bank Sta=316.8,336.8
XS Rating Curve= 0 ,0
Exp/Cntr=0.3,0.1

Type RM Length L Ch R = 1 ,25881.7 ,437.3,437.8,438.4
XS GIS Cut Line= 4
     1637235.773      298950.264     1637418.194      298951.596
     1637591.295      298944.938     1637824.316      298924.965
#Sta/Elev= 30
    10.1 1218.37    20.3 1214.81    50.7 1200.57    60.8 1192.08    70.9 1186.21
   131.8 1157.26   141.9 1148.68     152 1142.75   201.7 1119.12   211.3 1110.51
   220.5 1103.97  224.98 1102.59   230.5 1101.23   240.2 1101.89  242.87 1102.88
   249.8 1105.52     269 1116.38   278.7 1122.28   288.3 1130.29     346 1157.16
   355.7 1162.52   365.4 1170.03   423.9 1199.08   443.4  1214.1   492.1 1239.29
   501.8 1245.63   511.6 1255.05     570 1286.54   579.8 1295.61   589.5 1301.36
#Mann= 3 , 0 , 0
    10.1      .1       0  224.98    .045       0  242.87      .1       0
Bank Sta=224.98,242.87
XS Rating Curve= 0 ,0
Exp/Cntr=0.3,0.1

Type RM Length L Ch R = 1 ,25443.8 ,329.9,330.4,331
XS GIS Cut Line= 4
     1637239.767      299385.679     1637427.515      299387.011
      1637577.98      299385.679     1637813.663      299414.973
#Sta/Elev= 30
     9.9 1219.02    19.8 1213.21    29.6  1203.3    98.8 1166.44   108.7 1156.68
   118.6 1151.07     168 1127.26   177.9 1119.28   187.8 1113.36   217.8 1100.29
   227.9  1096.8   237.9 1094.93   247.9 1094.88   257.9 1095.63   288.1 1100.58
   298.1 1104.06   308.1 1109.83   318.2 1117.84   328.2 1129.08   338.2  1137.5
   387.7 1160.26   397.6 1166.28   407.5 1173.67     457 1199.87   466.9 1207.15
   476.8 1219.68   506.5 1239.91     546 1261.83   555.9 1272.48   575.7 1284.93
#Mann= 3 , 0 , 0
       0      .1       0   237.9    .045       0   257.9      .1       0
Bank Sta=237.9,257.9
XS Rating Curve= 0 ,0
Exp/Cntr=0.3,0.1

Type RM Length L Ch R = 1 ,25113.4 ,403.6,394.3,384.9
XS GIS Cut Line= 4
     1637222.457      299735.876     1637440.831      299715.903
     1637589.964      299718.566        1637811.      299775.822
#Sta/Elev= 30
      10 1212.45    19.9 1205.09    59.8 1186.44    79.7 1174.63    89.7 1166.86
   139.5 1145.33   149.5 1140.52   159.5 1132.64   219.3 1109.05   229.2  1101.4
   249.1 1092.73   259.1 1089.77     269 1088.81   288.8  1088.6   298.8 1088.21
   308.8 1088.57   318.7 1093.31   338.6 1108.97   348.6 1114.26   368.4 1122.28
   378.4 1128.53   388.3 1133.78   447.9 1158.15   457.8 1163.26   467.7 1170.09
   507.4 1186.41   527.3 1195.83   537.2 1206.37   547.1 1213.53   596.8 1244.16
#Mann= 3 , 0 , 0
       0      .1       0   288.8    .045       0   308.8      .1       0
Bank Sta=288.8,308.8
XS Rating Curve= 0 ,0
Exp/Cntr=0.3,0.1

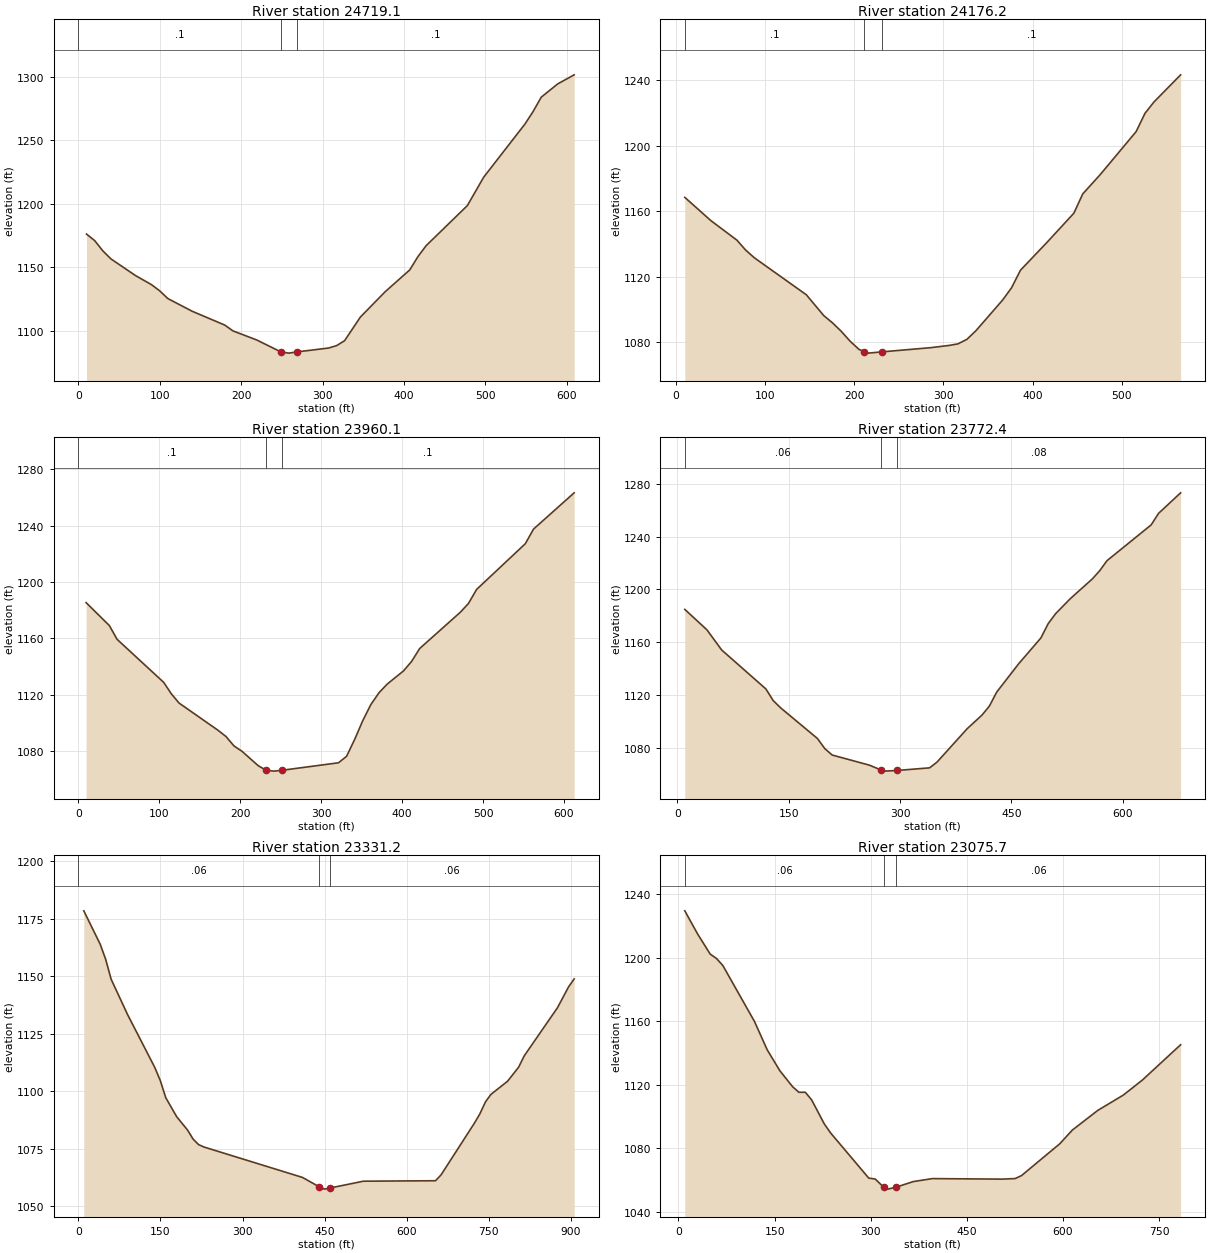
Type RM Length L Ch R = 1 ,24719.1 ,532.8,542.9,553.1
XS GIS Cut Line= 4
     1637316.997       300179.28      1637500.75      300131.344
     1637641.894      300063.436     1637898.882      300010.174
#Sta/Elev= 30
      10 1176.13      20    1171      30 1162.93      40 1156.55      70 1143.48
      90 1136.16    99.9 1131.38   109.9 1125.27   139.9 1115.23   179.9 1104.34
   189.9 1099.77   219.3 1092.56   248.4 1083.32   258.4 1082.24   268.4 1083.18
   307.4 1086.27   317.2 1088.15     327 1092.01   346.5 1110.73   376.8  1130.6
   407.1 1147.86   417.2 1158.41   427.3 1167.03   477.8 1198.53   497.9 1220.96
   548.4  1262.7   558.5  1272.6   568.6 1284.03   588.8 1294.48     609 1301.64
#Mann= 3 , 0 , 0
       0      .1       0   248.4    .045       0   268.4      .1       0
Bank Sta=248.4,268.4
XS Rating Curve= 0 ,0
Exp/Cntr=0.3,0.1

Type RM Length L Ch R = 1 ,24176.2 ,222.7,216.1,209.5
XS GIS Cut Line= 4
     1637391.564      300643.989     1637576.648      300641.326
     1637737.765      300650.647     1637954.807      300617.358
#Sta/Elev= 30
     9.7 1168.49      39 1154.25    68.2 1142.33    77.9 1136.32    87.7 1131.57
   146.1 1108.95   165.6 1096.25   175.4 1091.82   185.1 1086.72   195.2 1080.59
   205.3 1075.51  211.17 1074.25   215.4 1073.29  230.98 1074.06     286 1076.64
   306.1 1077.98   316.2 1078.94   326.3 1081.72   336.4 1086.99   366.5 1105.83
   376.4 1113.25   386.4 1123.97   416.4 1141.13   446.3 1158.81   456.3  1170.6
   476.2  1182.6   516.2 1208.69   526.1 1219.83   536.1 1226.72   566.1 1243.37
#Mann= 3 , 0 , 0
     9.7      .1       0  211.17    .045       0  230.98      .1       0
Bank Sta=211.17,230.98
XS Rating Curve= 0 ,0
Exp/Cntr=0.3,0.1

Type RM Length L Ch R = 1 ,23960.1 ,189.9,187.7,185.5
XS GIS Cut Line= 4
     1637383.205      300888.926     1637555.096      300875.174
     1637708.325      300832.938     1637987.281      300797.578
#Sta/Elev= 30
     9.6 1185.47    38.3 1169.21    47.9  1159.4   105.4  1128.9     115 1120.66
   124.5 1114.14   172.4 1094.91   182.4 1090.43   192.3 1083.72   202.2 1079.93
   222.1 1069.76     232 1066.45     242 1065.83     252 1066.46   321.4 1071.75
   331.4 1076.33   341.4 1088.32   351.5 1101.75   361.5 1113.18   371.6 1121.55
   381.6 1127.62   401.7 1136.95   411.7 1143.66   421.8 1152.92     472 1178.65
     482 1184.86   492.1 1194.84   552.3 1227.32   562.4 1237.67   612.6 1263.42
#Mann= 3 , 0 , 0
       0      .1       0     232    .045       0     252      .1       0
Bank Sta=232,252
XS Rating Curve= 0 ,0
Exp/Cntr=0.3,0.1

Type RM Length L Ch R = 1 ,23772.4 ,413.6,441.1,468.6
XS GIS Cut Line= 4
     1637391.564       301075.41     1637619.258      301056.768
     1637779.043      300992.854     1638045.352      300914.293
#Sta/Elev= 30
     9.9 1184.82    39.7 1169.37    59.6 1154.07   119.2 1124.57   129.1 1115.72
   139.1 1110.23   188.7 1087.02   198.7 1079.31   208.6  1074.5   258.8 1066.82
   274.2 1063.22   279.1 1062.31  295.66 1062.79   339.8 1064.79   349.9 1069.16
   390.4 1094.39   410.5 1104.77   420.4 1111.53   430.3 1122.16     460 1143.69
   489.8 1163.13   499.7    1174   509.6 1181.52   529.5 1192.93   559.2  1207.9
   569.1 1214.09     579 1221.74   638.5 1248.83   648.5 1257.57   678.2 1273.11
#Mann= 3 , 0 , 0
     9.9     .06       0   274.2    .045       0  295.66     .08       0
Bank Sta=274.2,295.66
XS Rating Curve= 0 ,0
Exp/Cntr=0.3,0.1

Type RM Length L Ch R = 1 ,23331.2 ,310.5,255.5,200.5
XS GIS Cut Line= 4
     1637403.547      301091.388     1637725.781      301327.072
     1637797.612      301437.385     1638154.671      301323.775
#Sta/Elev= 30
      10 1178.45    39.9 1163.94    49.9 1157.38    59.9  1148.7    89.8 1133.38
   139.7 1110.27   149.7  1104.6   159.7 1097.14   179.7 1088.86   199.6 1083.03
   209.6 1079.13   219.6 1076.74   229.6 1075.67   409.4 1062.45   439.9 1058.38
   449.9 1057.36   459.9 1057.86   520.7 1060.81   652.4 1061.01   662.5 1063.56
   723.3 1086.02   733.4 1090.11   743.5 1095.28   753.7  1098.6     784 1104.31
   804.3 1110.46   814.4 1115.34   875.2 1136.31   895.4 1145.35   905.6 1148.82
#Mann= 3 , 0 , 0
       0     .06       0   439.9    .045       0   459.9     .06       0
Bank Sta=439.9,459.9
XS Rating Curve= 0 ,0
Exp/Cntr=0.3,0.1

Type RM Length L Ch R = 1 ,23075.7 ,173.2,191.4,209.7
XS GIS Cut Line= 4
     1637644.107      301782.702     1637821.646      301583.063
      1637803.69      301445.189     1638164.201       301333.72
#Sta/Elev= 30
     9.9 1229.41    29.7 1214.99    49.5 1202.21    59.4 1199.42    69.3 1194.98
   118.7 1159.77   138.5 1141.97   158.3 1128.79   178.1 1118.77     188 1115.25
   197.9 1115.28   207.8  1110.5   227.6 1095.34   237.5 1089.64     297 1061.24
   306.9  1060.7  320.82 1055.37   326.8 1054.33  339.64 1055.56   366.5 1059.08
   396.3 1060.95   505.5 1060.62   525.4 1060.98   535.3 1062.84   594.9 1082.81
   614.7 1091.51   654.5  1103.9   694.2  1113.5     724 1122.97   783.6 1145.16
#Mann= 3 , 0 , 0
     9.9     .06       0  320.82    .045       0  339.64     .06       0
Bank Sta=320.82,339.64
XS Rating Curve= 0 ,0
Exp/Cntr=0.3,0.1

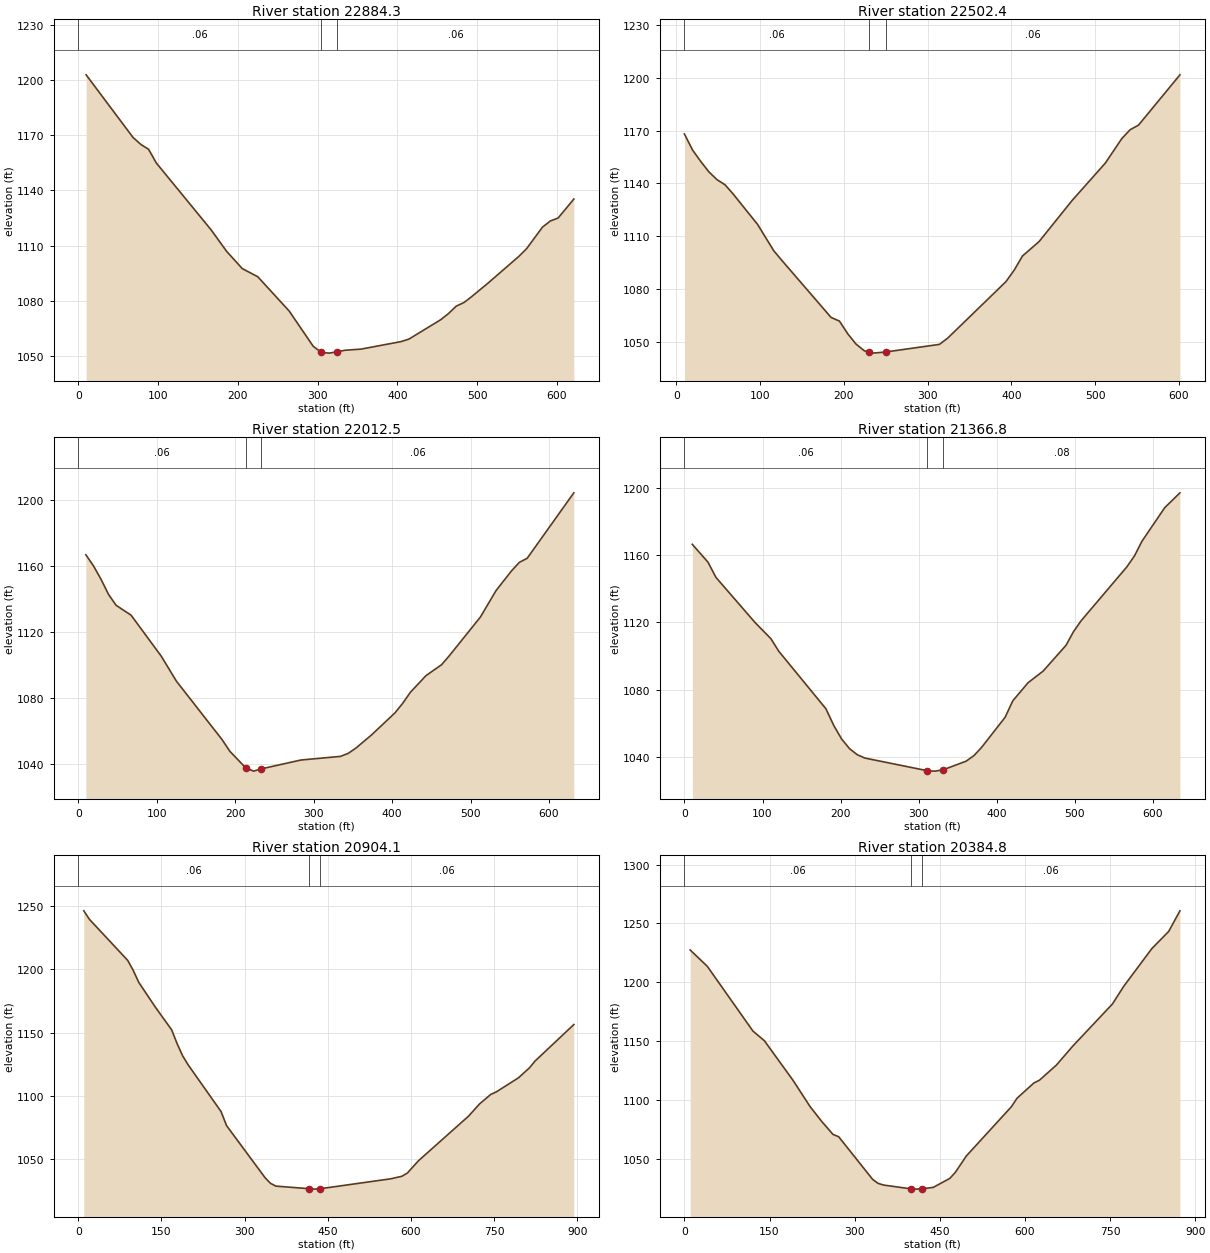
Type RM Length L Ch R = 1 ,22884.3 ,384.1,381.9,379.7
XS GIS Cut Line= 4
     1637743.091      301805.096     1637929.508      301631.995
      1638052.01      301500.172     1638167.854      301353.702
#Sta/Elev= 30
     9.8 1202.92    68.5 1168.89    78.3 1165.06    88.1 1162.37    97.8 1154.92
   166.3 1118.62   185.9 1106.85   205.5 1097.45     225 1092.99   264.4  1074.3
   294.4 1055.18   304.4 1051.87   314.4 1051.43   324.4 1052.18   334.4 1052.99
   354.4 1053.61   404.4 1057.69   414.4 1059.06     454 1069.55   463.8 1072.89
   473.7 1077.01   483.5 1078.99   493.3 1082.28     513 1089.33   552.3 1104.13
   562.1 1108.39   581.8 1120.01   591.6 1123.35   601.4 1124.97   621.1 1135.29
#Mann= 3 , 0 , 0
       0     .06       0   304.4    .045       0   324.4     .06       0
Bank Sta=304.4,324.4
XS Rating Curve= 0 ,0
Exp/Cntr=0.3,0.1

Type RM Length L Ch R = 1 ,22502.4 ,487.8,489.9,492
XS GIS Cut Line= 4
     1638042.689       302015.48     1638171.849      301912.951
     1638286.362      301762.487     1638434.163      301564.086
#Sta/Elev= 30
     9.7 1168.12    19.4    1159    29.1 1152.59    38.8 1146.65    48.5 1142.21
    58.2 1139.26    67.9 1134.02      97 1116.79   116.4 1101.78   126.1 1096.28
   184.8 1063.92   194.8 1061.84   204.7 1054.64   214.7 1048.74   224.6 1044.94
  230.58 1044.15   234.6 1043.64  249.93 1044.27   314.2 1048.61   324.1 1052.17
   393.6 1084.23   403.5 1090.79   413.4 1098.82   433.2 1107.01   472.7 1130.38
   512.3 1151.58   532.1 1165.59     542 1170.56   551.9 1173.13   601.4 1201.72
#Mann= 3 , 0 , 0
     9.7     .06       0  230.58    .045       0  249.93     .06       0
Bank Sta=230.58,249.93
XS Rating Curve= 0 ,0
Exp/Cntr=0.3,0.1

Type RM Length L Ch R = 1 ,22012.5 ,629.9,645.7,661.6
XS GIS Cut Line= 4
     1638283.699      302361.682     1638422.179      302257.821
     1638532.697      302140.645      1638707.13      301899.636
#Sta/Elev= 30
     9.6 1166.96    19.2  1160.3    28.9 1152.11    38.5 1142.89    48.1 1136.27
    67.3 1130.21   105.8 1105.26     125 1090.16   183.2 1054.64   193.2  1047.5
   213.4 1037.44   223.4 1035.44   233.4 1036.82   283.8 1042.19   334.2  1044.4
   344.1 1046.24     354 1049.48   373.8 1057.44   403.6 1070.82   413.5 1076.62
   423.4 1083.41   443.3 1093.51   463.1 1100.12     473 1105.59   512.7 1129.16
   532.5 1145.16   552.3 1157.18   562.3 1162.34   572.2 1164.79   631.7  1204.6
#Mann= 3 , 0 , 0
       0     .06       0   213.4    .045       0   233.4     .06       0
Bank Sta=213.4,233.4
XS Rating Curve= 0 ,0
Exp/Cntr=0.3,0.1

Type RM Length L Ch R = 1 ,21366.8 ,454.5,462.7,470.8
XS GIS Cut Line= 4
     1638608.596      302713.209     1638804.333      302633.317
     1639013.385      302627.991     1639195.807      302516.141
#Sta/Elev= 30
    10.1 1166.31    30.2 1155.71    40.3 1146.74    90.6 1119.86   110.7 1110.38
   120.8 1102.93   181.2 1068.79   191.3 1058.84   201.3 1050.87   211.4 1045.16
   221.4 1041.52   231.3 1039.56     311 1032.08     321 1031.83     331 1032.57
   360.8 1037.75   370.7 1041.02   380.7 1046.01   410.6 1063.73   420.5 1073.54
     440 1084.24   459.4 1091.17   488.6 1106.43   498.3 1114.59   508.1 1121.07
   566.4 1152.87   576.2 1159.38   585.9 1168.17   615.1 1188.08   634.5 1196.85
#Mann= 3 , 0 , 0
       0     .06       0     311    .045       0     331     .08       0
Bank Sta=311,331
XS Rating Curve= 0 ,0
Exp/Cntr=0.3,0.1

Type RM Length L Ch R = 1 ,20904.1 ,509.8,519.3,528.7
XS GIS Cut Line= 4
      1638577.97      302932.914     1638866.915      303036.775
     1639106.593      303128.652     1639360.918      303339.035
#Sta/Elev= 30
     9.9 1245.86    19.8 1239.28    89.1 1206.82      99 1199.03     109 1189.55
   138.7 1170.17   168.4 1152.09   178.3 1141.14   188.2 1131.64   198.1 1124.56
   257.5 1087.74   267.4 1076.67   336.7 1035.76   346.5 1031.25   356.4 1029.02
   415.5 1027.01   425.5 1026.65   435.5 1026.91   563.7 1034.79   583.7 1036.77
   593.7 1039.39   613.7 1049.05   703.8 1084.09   723.8 1093.77   743.8 1101.19
   753.8 1103.19   793.8 1114.28   813.8 1122.19   823.8 1127.51   893.8 1156.28
#Mann= 3 , 0 , 0
       0     .06       0   415.5    .045       0   435.5     .06       0
Bank Sta=415.5,435.5
XS Rating Curve= 0 ,0
Exp/Cntr=0.3,0.1

Type RM Length L Ch R = 1 ,20384.8 ,514.5,503.9,493.2
XS GIS Cut Line= 4
     1638446.147      303160.609     1638619.248       303420.26
     1638743.082      303557.409     1639055.994      303766.461
#Sta/Elev= 30
    10.1 1227.43    40.3 1213.53   120.8 1158.46   140.9  1150.3   191.3 1116.69
   221.5 1094.27   241.6 1081.91   261.7 1070.71   271.8 1068.72   331.5 1032.57
   341.2 1029.07     351 1027.64   399.3 1024.41   409.3 1024.18   419.3 1024.47
   438.5 1025.67   467.7 1033.29   477.4 1038.43   496.8 1052.36   576.1 1094.16
     586 1101.36   615.7 1114.35   625.6 1116.74   655.3  1129.5     685 1146.06
   754.3 1181.54   774.1 1196.51   823.6 1228.52   853.4  1243.2   873.2 1260.68
#Mann= 3 , 0 , 0
       0     .06       0   399.3    .045       0   419.3     .06       0
Bank Sta=399.3,419.3
XS Rating Curve= 0 ,0
Exp/Cntr=0.3,0.1

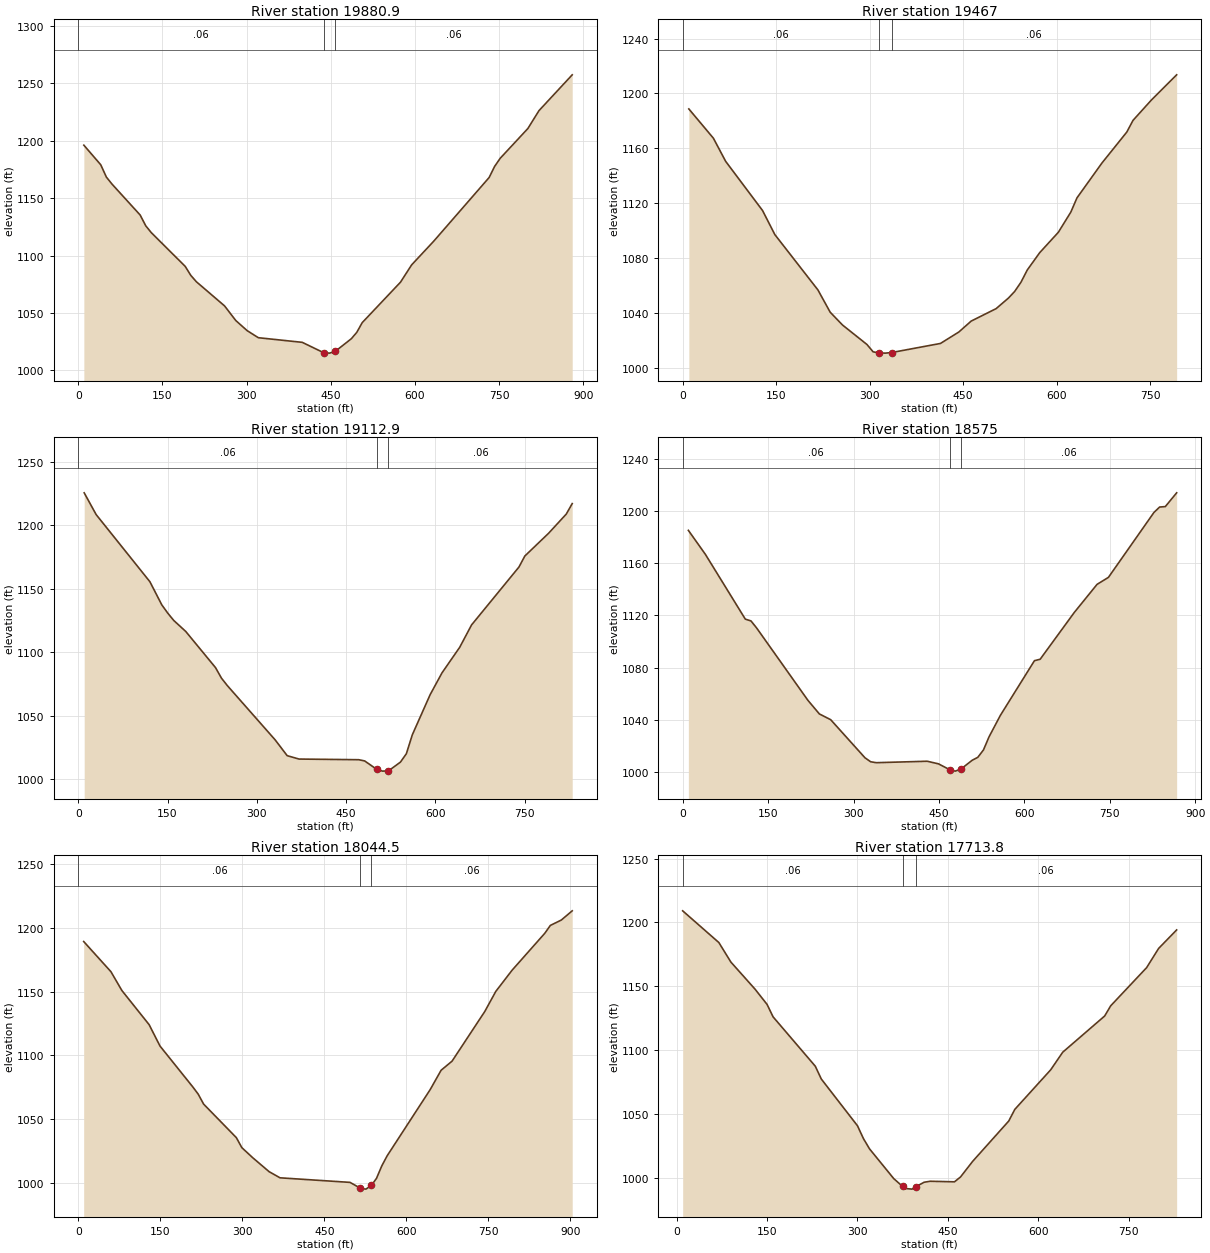
Type RM Length L Ch R = 1 ,19880.9 ,420.5,414,407.4
XS GIS Cut Line= 4
     1637977.443      303879.643     1638318.319      303878.311
     1638522.045      303942.225     1638838.953      304016.792
#Sta/Elev= 30
      10  1196.2    40.1 1179.14    50.1 1168.43    60.2 1162.28   110.3 1135.37
   120.3 1125.96   130.3 1119.95   190.5 1090.68   200.5 1082.82   210.5 1077.24
   260.7 1056.21   280.7 1043.46   300.8 1034.72   320.8 1028.52   399.1 1024.48
   437.6 1015.37   447.6 1015.09   457.6 1016.52   486.5 1027.63   496.2 1033.18
   505.9 1041.64   574.1 1076.88   593.9 1091.93   633.3 1112.58     732 1168.04
   741.8 1177.72   751.7 1184.77     801  1210.7   820.8 1226.28     880 1257.47
#Mann= 3 , 0 , 0
       0     .06       0   437.6    .045       0   457.6     .06       0
Bank Sta=437.6,457.6
XS Rating Curve= 0 ,0
Exp/Cntr=0.3,0.1

Type RM Length L Ch R = 1 ,19467   ,339.8,354,368.2
XS GIS Cut Line= 4
     1637929.508      304137.962     1638151.876      304244.486
     1638358.265       304239.16     1638656.531      304401.608
#Sta/Elev= 30
     9.9 1188.72    49.3 1167.37      69 1150.48   128.2 1114.61   147.9 1097.08
     217 1056.73   236.7 1040.47   256.4 1031.15   295.7 1016.91   305.6 1011.56
   315.2 1010.68   325.2  1010.6   335.2 1011.02   413.7 1017.66   443.2 1026.01
     463 1033.98     503 1043.05   522.9 1050.81   532.9 1055.66   542.9 1062.34
   552.9 1071.18   572.9 1083.85   602.9 1098.77   622.8 1113.41   632.8 1123.87
   672.8 1149.26   712.7 1171.84   722.7 1180.39   752.7 1195.48   792.7  1213.6
#Mann= 3 , 0 , 0
       0     .06       0   315.2    .045       0   335.2     .06       0
Bank Sta=315.2,335.2
XS Rating Curve= 0 ,0
Exp/Cntr=0.3,0.1

Type RM Length L Ch R = 1 ,19112.9 ,530.9,538,545.1
XS GIS Cut Line= 4
     1637825.647      304235.165     1638111.929      304486.827
     1638275.709       304618.65     1638482.099      304738.489
#Sta/Elev= 30
      10 1225.68    30.1 1208.55   120.4  1155.7   140.4 1137.49   150.5 1130.92
   160.5 1125.19   180.6 1116.56   230.7 1088.06   240.7 1079.75   250.8 1073.76
     331 1031.12   351.1 1018.73   371.1 1016.06   471.3 1015.55   481.3 1014.58
   501.3  1008.1   511.3 1006.56   521.3 1006.76   541.4 1013.64   551.4 1020.27
   561.4 1035.16   591.4 1066.81   611.3 1083.95   641.1 1104.11     661  1121.7
   740.6 1167.25   750.5 1175.93   790.3 1193.78   820.1 1208.95   830.1 1217.21
#Mann= 3 , 0 , 0
       0     .06       0   501.3    .045       0   521.3     .06       0
Bank Sta=501.3,521.3
XS Rating Curve= 0 ,0
Exp/Cntr=0.3,0.1

Type RM Length L Ch R = 1 ,18575   ,537.8,530.5,523.2
XS GIS Cut Line= 4
     1637547.354      304522.779     1637763.065      304835.692
     1637849.615      304979.499     1637914.861      305292.412
#Sta/Elev= 30
      10 1185.19      40 1166.72     110 1117.13     120 1115.74     130 1110.28
     220 1054.85     240 1044.47     260 1040.01   320.1 1010.86   330.1 1007.78
   340.1 1007.07   429.4 1008.18   449.2 1006.19   468.8 1001.74   478.8  1000.6
   488.8 1002.22   508.4 1008.91   518.3 1011.19   528.2 1016.82     538 1026.86
   557.9 1043.33   617.8 1085.29   627.8 1086.37   687.7 1122.22   727.7 1143.77
   747.7 1149.14   827.6 1198.89   837.6 1203.06   847.6 1203.41   867.5 1213.96
#Mann= 3 , 0 , 0
       0     .06       0   468.8    .045       0   488.8     .06       0
Bank Sta=468.8,488.8
XS Rating Curve= 0 ,0
Exp/Cntr=0.3,0.1

Type RM Length L Ch R = 1 ,18044.5 ,336.9,330.7,324.5
XS GIS Cut Line= 4
     1636890.903      305030.097     1637326.318      305083.359
     1637455.478      305185.888     1637695.156      305365.647
#Sta/Elev= 30
      10 1189.47    59.8 1165.77    79.8 1150.99   129.6 1124.18   149.5 1107.36
   209.4 1075.28   219.3  1069.6   229.3 1061.73   289.1 1035.39   299.1 1027.55
     319 1019.63   348.9 1008.69   368.9 1003.83   496.9 1000.24     516  995.64
     526  994.94     536  997.82   545.4 1003.46   555.1 1013.25   564.8  1021.1
   643.5 1073.12   663.5 1088.35   683.5 1095.48   743.4 1134.55   763.4 1150.24
   793.3 1166.96   853.2 1196.02   863.2 1202.13   883.2 1206.34   903.2  1213.6
#Mann= 3 , 0 , 0
       0     .06       0     516    .045       0     536     .06       0
Bank Sta=516,536
XS Rating Curve= 0 ,0
Exp/Cntr=0.3,0.1

Type RM Length L Ch R = 1 ,17713.8 ,284.2,283,281.8
XS GIS Cut Line= 4
     1636757.748      305241.813     1637062.672      305297.738
     1637259.741      305373.636     1637554.012      305465.512
#Sta/Elev= 30
      10 1209.11      70 1184.34      90 1169.06     130 1147.93     150 1135.99
     160 1126.25     230 1087.69     240 1077.66     300 1041.14     310    1031
   320.1 1023.02   360.3  999.77   374.9  993.72   380.4  992.06   390.5  991.62
  396.71  993.49   410.6     997   420.6  997.77   460.9  997.33   470.9  1001.1
     491 1013.28     551 1044.87     561 1053.93   620.6 1084.89   640.5 1098.62
   710.1 1126.93   720.1 1134.89   779.7 1164.72   799.6 1179.72   829.5 1194.18
#Mann= 3 , 0 , 0
      10     .06       0   374.9    .045       0  396.71     .06       0
Bank Sta=374.9,396.71
XS Rating Curve= 0 ,0
Exp/Cntr=0.3,0.1

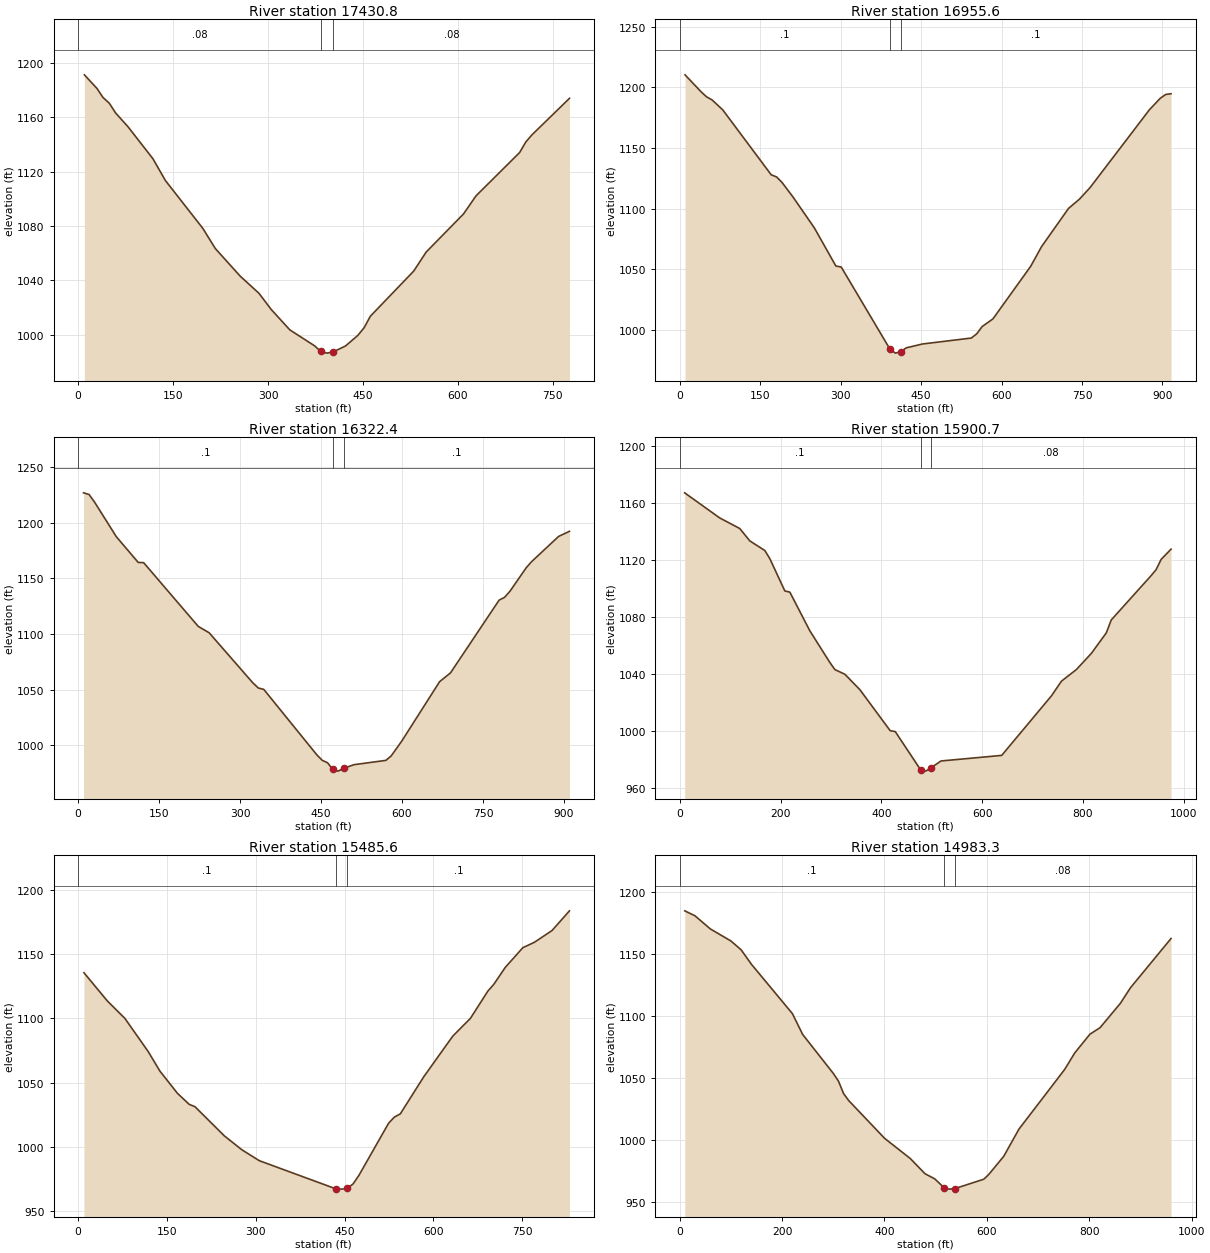
Type RM Length L Ch R = 1 ,17430.8 ,462.2,475.1,488.1
XS GIS Cut Line= 4
     1636675.193      305421.571     1636901.555       305541.41
     1637143.896       305618.64     1637391.564      305714.511
#Sta/Elev= 30
     9.9 1191.42    29.6  1181.5    39.4 1174.66    49.3 1170.49    59.1  1163.4
    78.8 1153.16   118.2 1129.55   137.9  1113.5     197 1078.25   216.7  1063.4
   256.1 1042.99   285.5 1030.48     305 1018.48   334.4 1003.43   373.5  991.68
   383.1  987.65   393.1  986.29   403.1  987.25   422.4  991.56     442  999.44
   451.8 1005.05   461.6 1013.49   530.1 1046.77   549.8 1060.81   608.8 1088.91
   628.5 1102.22   697.4 1134.15   707.2 1141.97     717 1147.25   776.1  1174.1
#Mann= 3 , 0 , 0
       0     .08       0   383.1    .045       0   403.1     .08       0
Bank Sta=383.1,403.1
XS Rating Curve= 0 ,0
Exp/Cntr=0.3,0.1

Type RM Length L Ch R = 1 ,16955.6 ,627.6,633.3,638.9
XS GIS Cut Line= 4
     1636510.081      305464.181     1636615.273      305757.121
     1636744.433      305938.211     1637020.063      306203.188
#Sta/Elev= 30
      10 1210.46    40.2 1196.35    50.2 1192.28    60.2 1189.83    80.3 1181.55
   170.7 1127.91   180.7 1126.18   190.8 1121.64   210.8 1109.92     251 1084.19
   291.2 1052.65   301.2  1051.8   392.2  983.92   402.2  980.74   412.2  981.97
   422.5  985.11   452.8   988.3   543.7  993.19   553.8  996.69   563.9 1002.68
     584    1009   654.4 1052.41   674.5 1068.55   724.9 1100.19     745 1107.72
   765.1 1117.39   875.8 1181.68   895.9 1191.07     906 1194.24     916 1194.87
#Mann= 3 , 0 , 0
       0      .1       0   392.2    .045       0   412.2      .1       0
Bank Sta=392.2,412.2
XS Rating Curve= 0 ,0
Exp/Cntr=0.3,0.1

Type RM Length L Ch R = 1 ,16322.4 ,415.3,421.6,428
XS GIS Cut Line= 4
     1635981.458       305661.25     1636072.003      306003.456
     1636153.227      306235.145     1636239.777      306533.411
#Sta/Elev= 30
    10.1 1226.96    20.2 1225.49    30.3 1218.75    70.8 1187.49   111.3 1164.37
   121.4 1164.13   222.5 1106.81   242.7 1101.08   323.6 1056.04   333.8 1051.37
   343.9 1050.14   442.4  991.13   452.2  986.33     462  984.15   471.6  978.15
   481.7  976.61   491.6   979.1   511.1  982.42     570  986.27   579.9  990.28
   599.5 1003.67   669.6 1057.09   689.7 1064.96   779.8 1130.44   789.8 1132.91
   799.9 1138.44   829.9  1159.5   839.9 1165.03     890 1187.75   910.1 1192.34
#Mann= 3 , 0 , 0
       0      .1       0   471.6    .045       0   491.6      .1       0
Bank Sta=471.6,491.6
XS Rating Curve= 0 ,0
Exp/Cntr=0.3,0.1

Type RM Length L Ch R = 1 ,15900.7 ,415.6,415.1,414.6
XS GIS Cut Line= 4
      1635828.33      305751.795      1635724.47      306135.279
     1635729.796      306346.995      1636026.73      306560.042
#Sta/Elev= 30
     9.9 1167.28    79.5 1149.62   119.2 1142.19   139.1 1133.51   168.9 1126.74
   178.8 1121.04   208.6 1098.31   218.5  1097.5   258.2 1070.29     298 1047.97
   307.9 1043.04   327.8 1039.73   357.6 1028.85   417.5 1000.12   427.6  999.46
   478.1  972.48   488.1  971.68   498.1  973.99   518.3  978.81   638.7  982.74
   737.5 1024.66   757.2 1034.91   786.9  1043.1   816.5 1054.44   846.1 1068.83
     856 1077.94     935 1109.08   944.9 1113.28   954.8 1120.45   974.5  1127.7
#Mann= 3 , 0 , 0
       0      .1       0   478.1    .045       0   498.1     .08       0
Bank Sta=478.1,498.1
XS Rating Curve= 0 ,0
Exp/Cntr=0.3,0.1

Type RM Length L Ch R = 1 ,15485.6 ,513.9,502.3,490.7
XS GIS Cut Line= 4
     1635230.467      306046.066     1635404.899      306344.332
     1635416.883      306562.705     1635516.749      306809.041
#Sta/Elev= 30
     9.9 1135.48    49.4  1113.5      79 1099.95   118.5 1074.03   138.2 1058.88
   167.8 1041.59   187.6 1033.03   197.4 1031.18   246.8 1008.56   276.4  997.72
     306  989.16   434.9  967.31   444.9     967   454.9  967.52   464.8  971.21
   474.8  978.08   524.5 1018.33   534.4 1023.13   544.3 1025.62   583.9 1054.48
   623.3 1079.94   633.1 1086.21   662.7 1099.96   692.2  1121.2   702.1 1126.39
   721.7 1139.72   751.3 1154.99     771 1159.23   800.5  1168.3     830 1183.67
#Mann= 3 , 0 , 0
       0      .1       0   434.9    .045       0   454.9      .1       0
Bank Sta=434.9,454.9
XS Rating Curve= 0 ,0
Exp/Cntr=0.3,0.1

Type RM Length L Ch R = 1 ,14983.3 ,324.4,323.1,321.8
XS GIS Cut Line= 4
     1634537.601      306354.265     1634941.521      306553.384
     1635033.398      306687.871     1635295.712      306914.233
#Sta/Elev= 30
      10 1185.12      30 1181.09      60 1170.48   100.1 1160.79   120.1 1153.64
   140.1 1142.01   220.2 1102.13   240.2 1085.35   300.2 1053.83   310.2  1047.6
   320.2 1037.56   330.2 1031.94   400.3 1001.46   450.3  985.22   479.1  972.93
   498.2  968.74     517  961.41     527  960.46     537  960.82     594  968.46
   603.6  972.25     633  986.97   662.7 1008.91   751.8 1056.98   771.6 1070.37
   801.3 1085.53   821.1  1090.8   860.7 1110.41   880.5 1123.03   959.7 1162.77
#Mann= 3 , 0 , 0
       0      .1       0     517    .045       0     537     .08       0
Bank Sta=517,537
XS Rating Curve= 0 ,0
Exp/Cntr=0.3,0.1