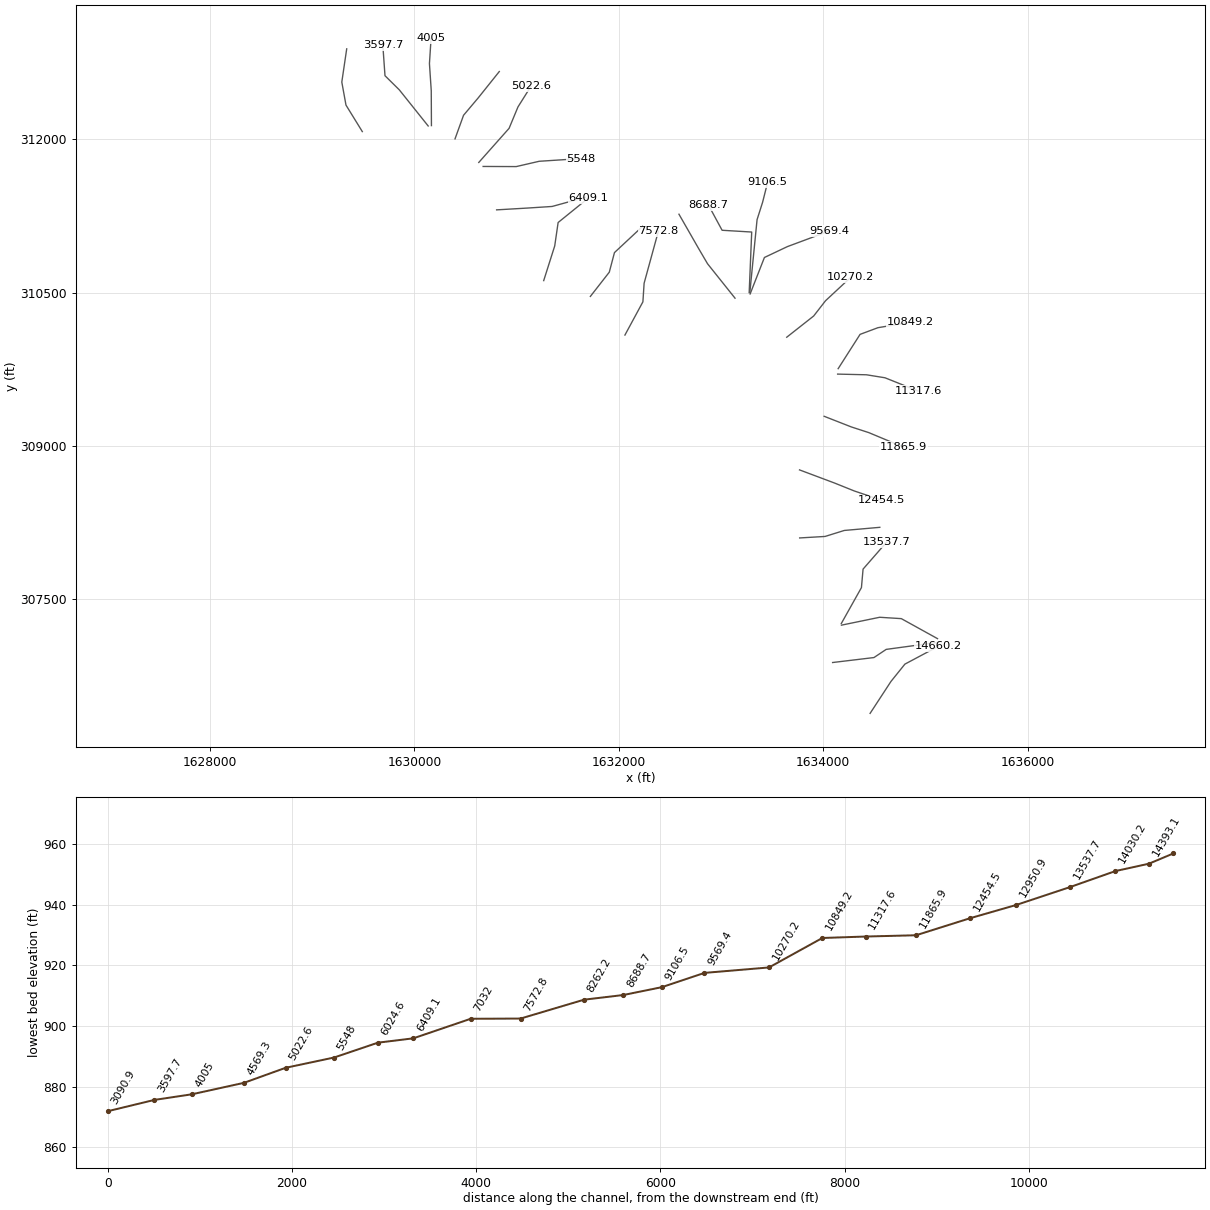
HEC-RAS study lrlfrk.prj: lrlfrk

--- lrlfrk.g01 (geometry) --- (continued)

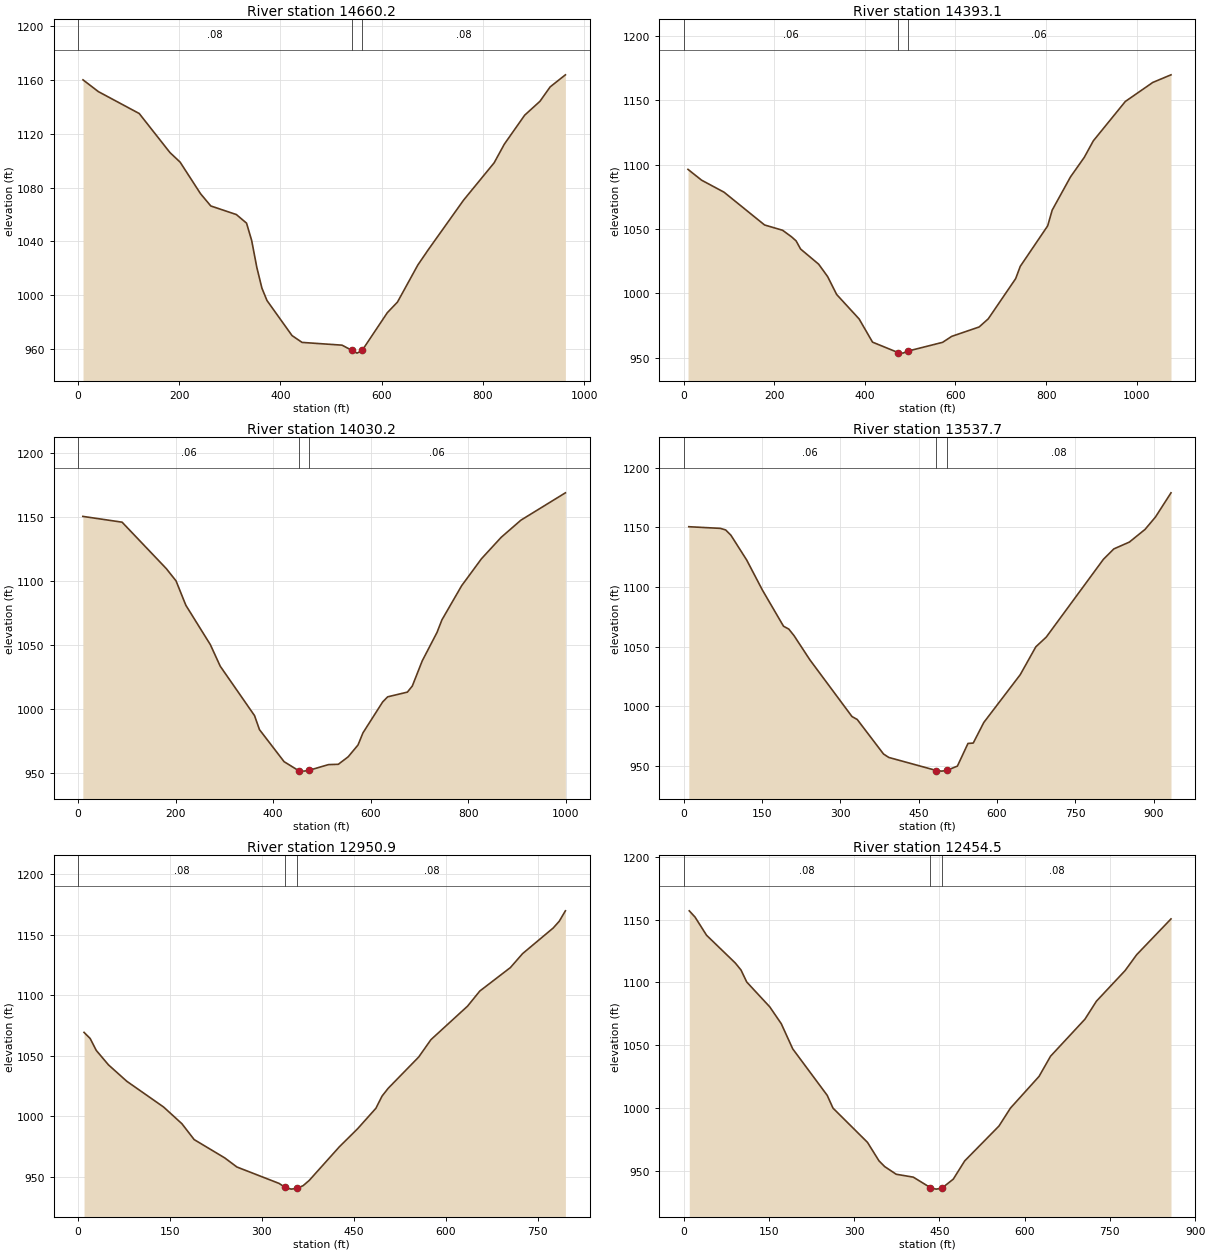
Type RM Length L Ch R = 1 ,14660.2 ,273.3,267.1,261.1
XS GIS Cut Line= 4
     1634459.022       306383.95     1634663.327       306696.52
      1634799.53      306865.901     1635127.816      307040.521
#Sta/Elev= 30
    10.1 1160.14    40.4 1151.38   121.1 1135.09   181.7 1106.09   201.8 1098.96
   242.2 1075.44   262.4 1066.36   312.9 1059.97     333 1053.58   343.1  1040.7
   353.2 1020.81   363.3 1005.28   373.4  996.01   422.8  969.99   442.6   964.9
   521.6  962.85   541.2  958.93   551.2  956.93   561.2   958.9   610.9  986.96
     631  994.89   671.2 1022.44   691.3 1033.53   761.6 1070.72   821.9 1098.44
     842  1112.3   882.2 1133.86   912.4 1144.19   932.5  1154.9   962.6 1163.87
#Mann= 3 , 0 , 0
       0     .08       0   541.2    .045       0   561.2     .08       0
Bank Sta=541.2,561.2
XS Rating Curve= 0 ,0
Exp/Cntr=0.3,0.1

Type RM Length L Ch R = 1 ,14393.1 ,375.9,362.9,349.7
XS GIS Cut Line= 4
      1634092.32      306881.617     1634496.785      306930.211
     1634616.624      307010.104     1635135.927      307080.676
#Sta/Elev= 30
     9.9 1096.23    39.7 1087.88    89.4 1078.51   178.8 1053.05   218.6 1048.94
   238.5  1043.8   248.4 1040.69   258.3 1034.36   298.1 1022.62     318 1012.94
   337.8  999.09   387.5  980.02     417  962.05   474.2  953.83   484.2  953.52
   494.2  955.02   571.6   961.9   591.7  966.54   652.2  973.83   672.3  980.14
   732.8 1011.39   742.9  1020.9   803.4 1052.36   813.4  1064.6   853.8 1090.42
     884 1105.49   904.1 1118.39   974.7 1148.96  1035.2 1163.74  1075.5 1169.67
#Mann= 3 , 0 , 0
       0     .06       0   474.2    .045       0   494.2     .06       0
Bank Sta=474.2,494.2
XS Rating Curve= 0 ,0
Exp/Cntr=0.3,0.1

Type RM Length L Ch R = 1 ,14030.2 ,461.4,492.5,523.6
XS GIS Cut Line= 4
     1634178.546      307247.119      1634552.71      307324.349
     1634764.426      307311.033     1635118.617      307115.296
#Sta/Elev= 30
    10.1 1150.28    90.5 1145.76     181  1109.5   201.1 1099.84   221.2 1080.78
   271.5 1049.91   291.6 1033.16   361.9  994.52     372  983.58   422.5  958.48
   452.9  951.33   462.9   951.1   472.9  951.65   513.4  956.19   533.6  956.44
   553.8   962.3     574  971.56   584.1  981.02   624.5 1005.22   634.7 1009.19
   675.1 1012.88   685.2 1017.63   705.5 1037.28   735.8 1059.53   745.9 1069.38
   786.4 1096.12   826.9 1117.15   867.3 1133.91   907.8 1147.34   998.9 1168.71
#Mann= 3 , 0 , 0
       0     .06       0   452.9    .045       0   472.9     .06       0
Bank Sta=452.9,472.9
XS Rating Curve= 0 ,0
Exp/Cntr=0.3,0.1

Type RM Length L Ch R = 1 ,13537.7 ,610.3,586.9,563.4
XS GIS Cut Line= 4
     1634177.215      307263.098     1634374.283      307614.626
     1634390.262      307795.716     1634619.287       308058.03
#Sta/Elev= 30
    10.1 1150.57    70.5 1149.18    80.6 1147.87    90.7 1143.45   120.9 1122.67
   151.1 1097.41   191.4 1067.21   201.5 1064.81   211.6 1059.27   241.8 1039.09
   322.4  991.56   332.5  989.08   382.8  960.15   392.9  957.28   483.9  946.34
   493.9  945.82   503.9  946.39   524.2  950.04   544.4  968.99   554.5  969.33
   574.7  986.57   644.5 1026.64   674.3 1049.97   694.2 1058.08   803.7 1123.31
   823.6 1131.98   853.4 1137.72   883.3 1148.32   903.2 1158.66     933 1178.96
#Mann= 3 , 0 , 0
       0     .06       0   483.9    .045       0   503.9     .08       0
Bank Sta=483.9,503.9
XS Rating Curve= 0 ,0
Exp/Cntr=0.3,0.1

Type RM Length L Ch R = 1 ,12950.9 ,510.1,496.4,482.7
XS GIS Cut Line= 4
     1633769.762      308100.639     1634018.761      308115.286
     1634206.509      308173.874     1634554.042        308204.5
#Sta/Elev= 30
      10 1069.26      20 1064.22    29.9 1054.41    49.9 1042.43    79.8 1028.88
   139.7 1007.68   169.6  993.88   189.6  980.78   239.5  965.65   259.3  958.15
   328.1   944.6   337.8  941.34   347.8  939.89   357.8  940.58   367.4  942.81
   377.3  947.12   426.4  974.85   456.1  989.71     486 1006.64   495.9  1016.6
   505.9 1023.06   555.8 1048.95   575.7 1063.25   635.5 1090.96   655.4 1103.39
   705.3 1122.76   725.2 1134.29   775.1 1155.42     785 1161.02     795 1169.61
#Mann= 3 , 0 , 0
       0     .08       0   337.8    .045       0   357.8     .08       0
Bank Sta=337.8,357.8
XS Rating Curve= 0 ,0
Exp/Cntr=0.3,0.1

Type RM Length L Ch R = 1 ,12454.5 ,587.1,588.5,589.9
XS GIS Cut Line= 4
      1633768.43      308766.412     1634109.306      308638.583
     1634305.043      308560.022     1634572.683      308469.477
#Sta/Elev= 30
    10.1 1156.95    20.2 1152.02    40.5 1137.53      91 1115.48   101.1 1109.88
   111.2 1100.31   151.7 1080.55   171.9 1067.18   192.1 1047.14   252.8 1010.14
   262.9 1000.02   323.6  972.76   343.8  958.08   353.9  953.47   374.1   947.4
   404.2  945.09   434.4  936.71   444.4  935.56   454.4  936.29   474.5   943.5
   494.6  958.01   554.9  985.75     575  999.98   625.4 1025.24   645.6 1041.28
   706.1 1070.73   726.3 1085.06   776.8 1109.44     797 1121.99   857.5 1150.52
#Mann= 3 , 0 , 0
       0     .08       0   434.4    .045       0   454.4     .08       0
Bank Sta=434.4,454.4
XS Rating Curve= 0 ,0
Exp/Cntr=0.3,0.1

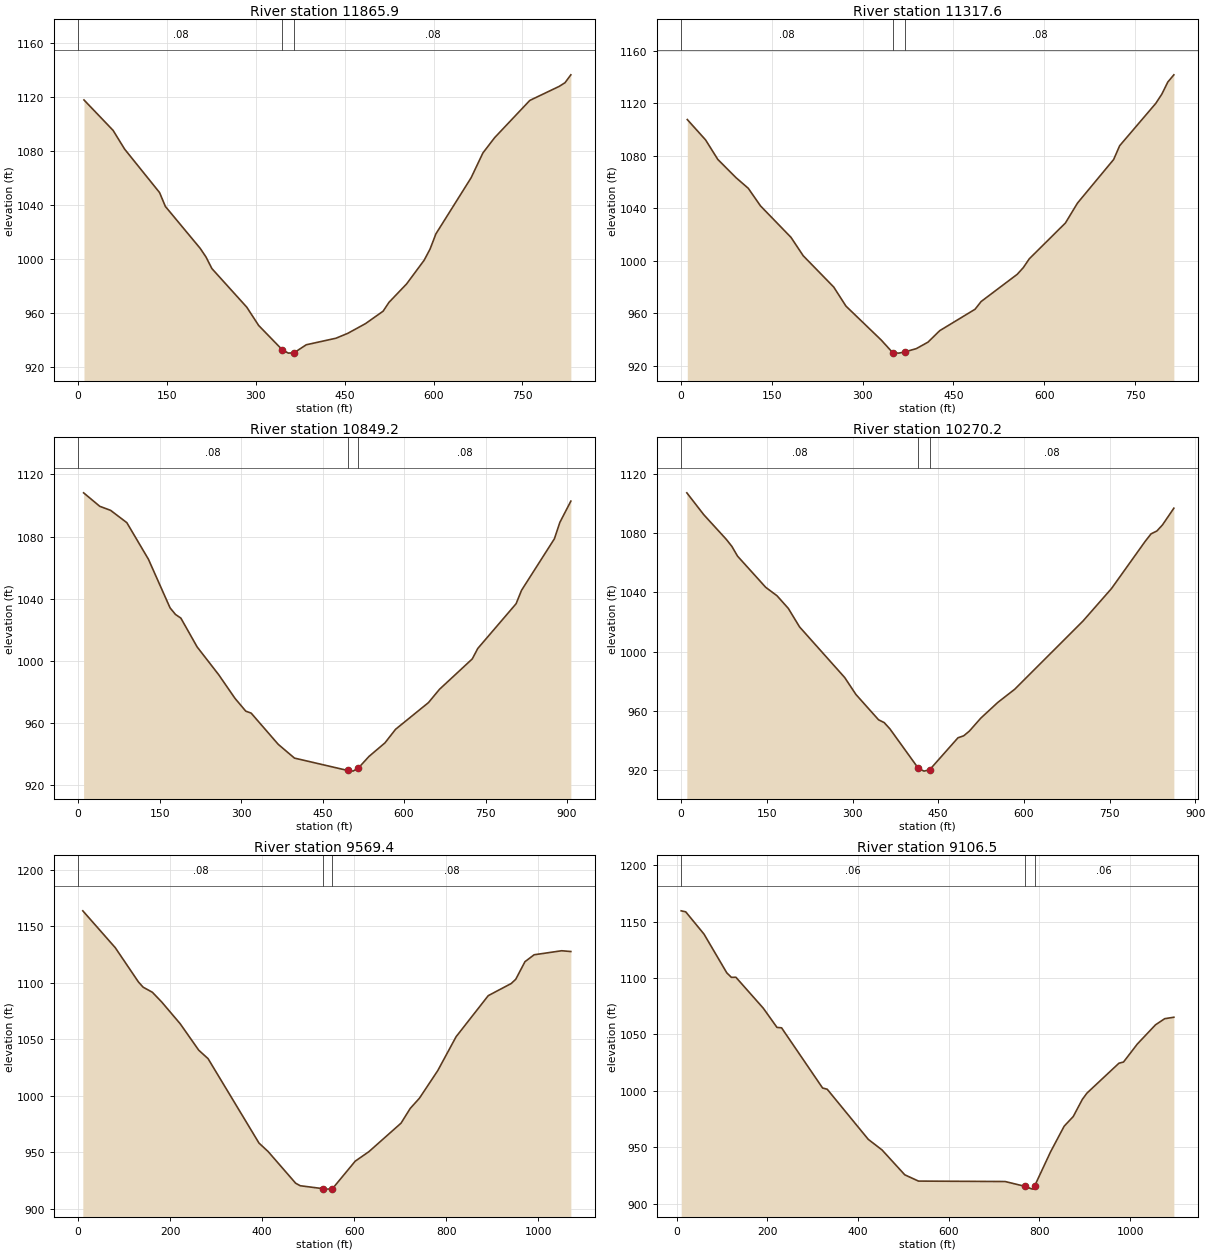
Type RM Length L Ch R = 1 ,11865.9 ,545.2,548.3,551.4
XS GIS Cut Line= 4
      1634009.44       309291.04     1634274.418       309187.18
     1634446.187      309131.255     1634784.399      308990.111
#Sta/Elev= 30
     9.8 1117.61    58.9 1095.07    78.5  1081.1   137.4 1048.95   147.2 1038.66
   206.1 1007.53   215.9  1001.1   225.7  992.62   284.6  963.99   304.7  950.42
   344.9  932.24   354.9  929.92   364.9  930.31     385  936.11   435.1  940.96
   455.2  944.61   485.1  951.81   514.8  961.02   524.7  967.57   554.4  981.21
   584.1  998.82     594 1007.04   603.9 1018.34   663.3  1059.9   683.2 1078.28
     703 1089.64   762.4 1117.25   811.9 1127.63   821.8 1130.37   831.7 1136.23
#Mann= 3 , 0 , 0
       0     .08       0   344.9    .045       0   364.9     .08       0
Bank Sta=344.9,364.9
XS Rating Curve= 0 ,0
Exp/Cntr=0.3,0.1

Type RM Length L Ch R = 1 ,11317.6 ,458,468.5,478.9
XS GIS Cut Line= 4
     1634141.263      309703.819     1634423.551      309697.161
      1634604.64      309667.867     1634928.206      309538.708
#Sta/Elev= 30
    10.1 1107.41    40.3 1091.94    60.5 1077.08    90.8 1063.07   110.9 1055.05
   131.1 1041.64   181.5 1017.67   201.7 1003.66   252.1  979.84   272.3  965.32
   330.6  939.46   349.6  929.84   359.6   929.5   369.6  930.44   388.6  932.93
   407.9  937.87   427.2  946.58   485.7  962.93   495.7  968.81   555.4  989.55
   565.4  994.64   575.3 1001.36     635 1028.63   654.9 1043.77   714.7    1077
   724.6 1087.46   784.3 1119.72   794.3 1126.76   804.2 1135.99   814.2 1141.49
#Mann= 3 , 0 , 0
       0     .08       0   349.6    .045       0   369.6     .08       0
Bank Sta=349.6,369.6
XS Rating Curve= 0 ,0
Exp/Cntr=0.3,0.1

Type RM Length L Ch R = 1 ,10849.2 ,567.7,579,590.2
XS GIS Cut Line= 4
     1634146.589      309757.081     1634360.968       310092.63
       1634535.4      310157.876     1634853.639      310211.138
#Sta/Elev= 30
      10 1108.18    39.8 1099.49    59.7  1096.9    89.6 1088.97   129.4 1065.38
   169.2 1034.11   179.2 1029.87   189.1 1027.51     219 1008.99   258.8  991.05
   288.7  975.88   308.6  967.63   318.5  966.36   368.3  946.28   398.2  937.41
     496  929.46     506  929.02     516  931.05   535.4  938.47   564.8  947.19
   584.4  955.96   644.9  973.12   665.1  981.64   725.6 1001.26   735.7 1007.96
   806.3  1036.8   816.3 1045.43   876.8 1078.59   886.9 1089.18   907.1 1102.83
#Mann= 3 , 0 , 0
       0     .08       0     496    .045       0     516     .08       0
Bank Sta=496,516
XS Rating Curve= 0 ,0
Exp/Cntr=0.3,0.1

Type RM Length L Ch R = 1 ,10270.2 ,710.1,700.7,691.4
XS GIS Cut Line= 4
     1633643.265      310064.668     1633906.911      310272.389
     1634022.756      310421.522     1634270.423      310651.879
#Sta/Elev= 30
     9.9 1107.24    39.5  1092.5      79 1075.82    88.8 1071.05    98.7 1064.49
   148.1  1043.4   167.8 1037.74   187.6 1029.19   207.3 1016.69   286.3  982.52
     306  971.07   345.6  953.97   355.5  952.07   365.5  947.83   415.1   921.3
   425.1   919.3   435.1  920.22   484.7  941.82   494.7  943.15   504.6  946.32
   524.5  955.02   554.3  965.66   584.2  974.65   703.6 1020.67   753.3 1042.51
     813 1074.75   822.9 1079.58   832.9 1081.44   842.8 1085.59   862.7 1096.86
#Mann= 3 , 0 , 0
       0     .08       0   415.1    .045       0   435.1     .08       0
Bank Sta=415.1,435.1
XS Rating Curve= 0 ,0
Exp/Cntr=0.3,0.1

Type RM Length L Ch R = 1 ,9569.4  ,446.4,462.9,479.4
XS GIS Cut Line= 4
      1633285.08      310488.099     1633424.892      310844.953
     1633649.923      310951.477      1634061.37      311104.604
#Sta/Elev= 30
    10.1 1163.84    80.7 1131.18   131.1 1100.85   141.2 1096.27   161.4 1091.74
   181.5 1083.21   221.9 1063.85   262.2 1040.45   282.4 1033.02   393.2  958.25
   413.1  950.74   472.9  922.73   482.9   920.5   532.6  917.89   542.6   917.5
   552.6  917.73   602.4  942.25   632.2  950.67   702.1  975.91     722  988.92
     742  997.95   781.9  1022.4   821.8 1052.43   891.7 1088.76   941.5 1099.47
   951.5 1103.26   971.5 1118.81   991.4 1124.94  1051.3  1128.5  1071.3 1127.81
#Mann= 3 , 0 , 0
       0     .08       0   532.6    .045       0   552.6     .08       0
Bank Sta=532.6,552.6
XS Rating Curve= 0 ,0
Exp/Cntr=0.3,0.1

Type RM Length L Ch R = 1 ,9106.5  ,381,417.8,454.6
XS GIS Cut Line= 4
     1633282.417      310504.077     1633352.989      311215.122
     1633407.582      311386.892     1633456.849      311582.629
#Sta/Elev= 30
    10.1 1159.69    20.1 1158.81    60.4 1139.07   110.7 1104.67   120.8 1100.68
   130.8 1100.75   191.2 1073.29   221.4 1056.26   231.5 1055.89     322 1002.48
   332.1 1001.43   422.7  956.94   452.9  947.61   503.2  925.49   533.4  919.92
   724.6  919.53  768.34  915.24   784.6  912.79  789.58  915.62   824.7  945.88
   854.7  968.63   874.7   977.2   894.8  992.43   904.9  997.95   975.5  1024.5
   985.6 1025.56  1015.9 1041.46  1056.2  1058.6  1076.4    1064  1096.6 1065.28
#Mann= 3 , 0 , 0
    10.1     .06       0  768.34    .045       0  789.58     .06       0
Bank Sta=768.34,789.58
XS Rating Curve= 0 ,0
Exp/Cntr=0.3,0.1

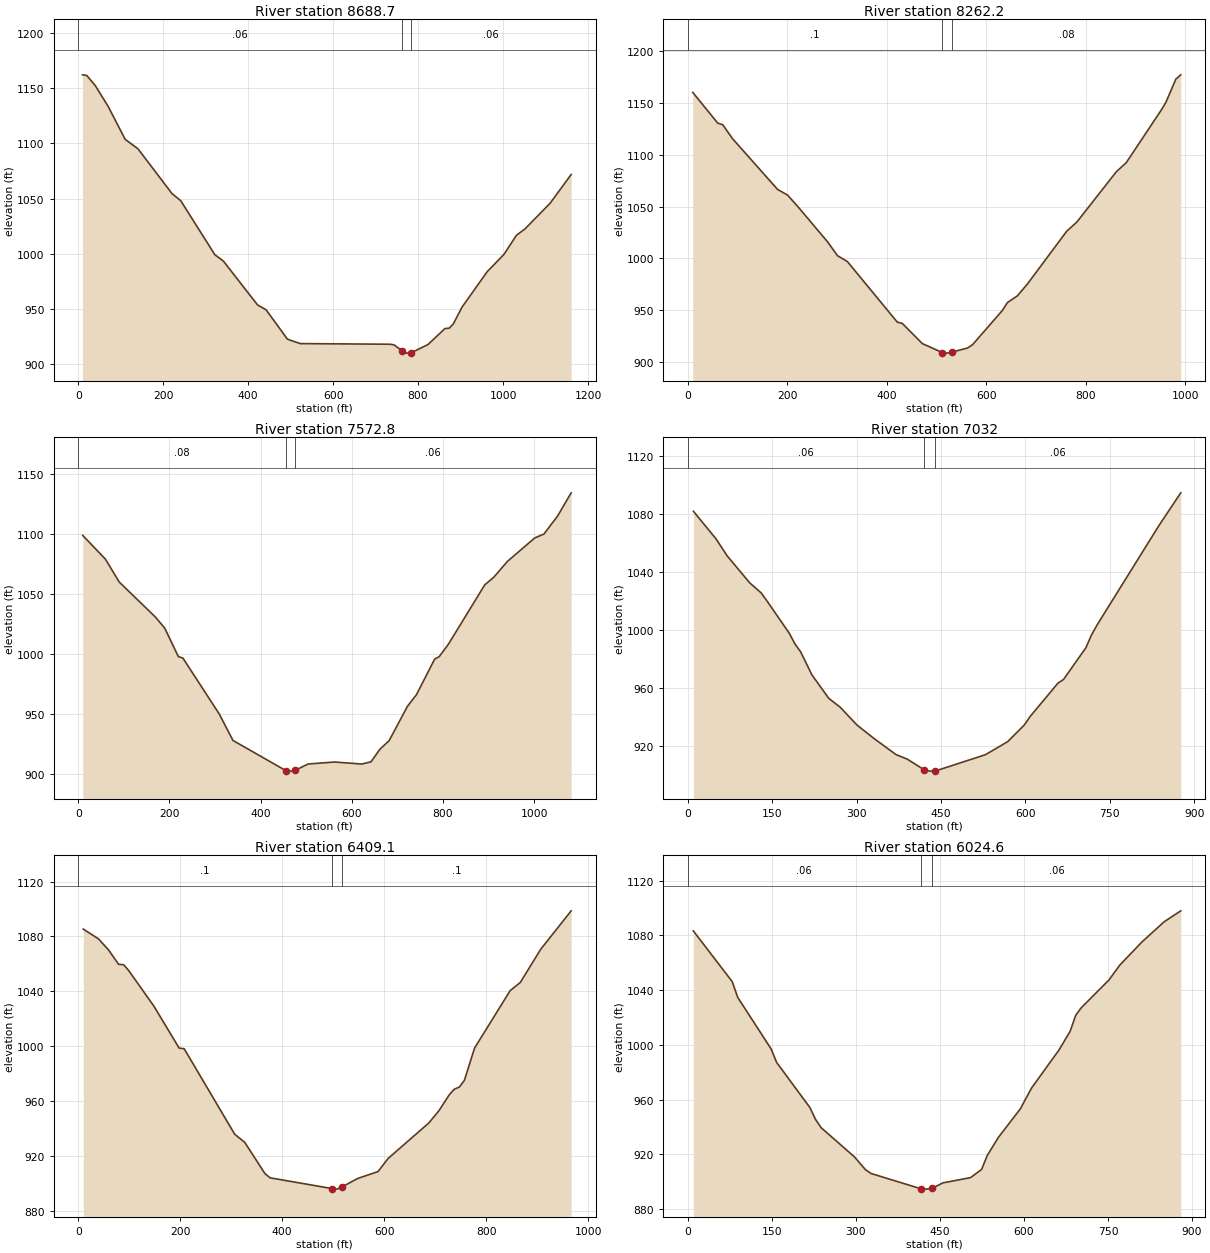
Type RM Length L Ch R = 1 ,8688.7  ,446.3,426.5,406.6
XS GIS Cut Line= 4
     1633275.759      310501.414       1633300.5      311093.975
     1633010.782      311111.262     1632878.959      311354.935
#Sta/Elev= 30
    10.1 1161.84    20.1 1161.31    40.2 1152.14    70.4 1133.38   110.6  1103.5
   140.7 1094.97   221.1 1054.33   241.3 1048.09   321.7  999.19   341.8  993.43
   422.2  953.78   442.3   949.4   492.6   922.8   522.7  918.82   733.2  918.24
   743.2  917.72   763.2  912.13   773.2   910.2   783.2  910.42   823.3  917.94
   863.3  932.41   873.3  932.76   883.3   936.8   903.1  951.52   962.5  983.73
    1002   999.4  1031.7 1016.79  1051.5 1022.46  1110.9 1045.75  1160.4 1071.72
#Mann= 3 , 0 , 0
       0     .06       0   763.2    .045       0   783.2     .06       0
Bank Sta=763.2,783.2
XS Rating Curve= 0 ,0
Exp/Cntr=0.3,0.1

Type RM Length L Ch R = 1 ,8262.2  ,701.4,689.4,677.4
XS GIS Cut Line= 4
     1633137.278      310446.821     1632868.306      310783.702
     1632781.756      310931.503     1632588.682      311268.384
#Sta/Elev= 30
      10 1160.18    60.2 1130.59    70.2    1129    90.2  1115.4   180.5 1066.57
   200.5 1061.15   220.6 1050.35   280.7 1016.16   300.8 1002.71   320.8  996.96
   421.1  938.49   431.1  937.32   471.4  917.82   511.8   909.2   521.8  908.66
   531.8  909.78   562.1  913.59   572.1  916.74   632.2  949.84   642.2  957.41
   662.1  963.84     682  975.05   761.7 1026.42   781.6 1035.01   861.2  1083.7
   881.1 1092.44   950.8 1142.72   960.8 1150.66   980.7 1173.02   990.6 1177.16
#Mann= 3 , 0 , 0
       0      .1       0   511.8    .045       0   531.8     .08       0
Bank Sta=511.8,531.8
XS Rating Curve= 0 ,0
Exp/Cntr=0.3,0.1

Type RM Length L Ch R = 1 ,7572.8  ,544.1,540.8,537.4
XS GIS Cut Line= 4
     1632060.059      310085.973     1632235.823      310410.869
     1632247.806      310593.291     1632387.619      311103.273
#Sta/Elev= 30
      10 1098.91    59.9 1079.04    89.9  1060.1   169.7 1030.71   189.7 1021.67
   219.6  997.93   229.6  996.65   309.5  949.96   339.4     928   455.6   902.8
   465.6  902.43   475.6  903.06   504.1  908.37   562.2  910.02     622  908.34
     642  910.15     662  920.87   681.9  927.84   721.8  956.34   741.8  966.17
   781.7  995.83   791.7  997.88   811.6 1008.09   891.4 1057.62   911.4 1064.08
   941.3 1077.27  1001.2 1096.81  1021.1    1100  1051.1 1114.95    1081  1134.4
#Mann= 3 , 0 , 0
       0     .08       0   455.6    .045       0   475.6     .06       0
Bank Sta=455.6,475.6
XS Rating Curve= 0 ,0
Exp/Cntr=0.3,0.1

Type RM Length L Ch R = 1 ,7032    ,620.6,622.9,625.2
XS GIS Cut Line= 4
     1631721.846      310464.131     1631906.931      310701.146
      1631957.53      310892.889     1632233.159      311149.877
#Sta/Elev= 30
      10 1081.75    50.1 1062.74    70.2 1050.85   110.3 1032.22   130.3 1025.44
   140.3 1020.08   180.4   997.5   190.5   990.1   200.5  984.73   220.5  968.84
   250.6  952.57   270.6  946.55   300.7  934.16   330.5  924.99   370.1  913.75
     390  910.63   419.6  903.39   429.6  902.36   439.6  902.42   528.8  913.69
   568.4  922.71   598.2  934.34   608.1  939.99   657.7   963.1   667.6  965.65
   707.3  987.51   717.2  996.28   727.1 1003.19   836.2 1071.32   875.9 1094.48
#Mann= 3 , 0 , 0
       0     .06       0   419.6    .045       0   439.6     .06       0
Bank Sta=419.6,439.6
XS Rating Curve= 0 ,0
Exp/Cntr=0.3,0.1

Type RM Length L Ch R = 1 ,6409.1  ,412.5,384.6,356.6
XS GIS Cut Line= 4
     1631265.126       310618.59     1631372.982      310958.134
      1631406.27       311187.16     1631700.542      311425.506
#Sta/Elev= 30
     9.9 1085.39    39.6 1078.28    59.4 1070.24    79.2 1059.73    89.1 1059.39
      99 1055.17   148.4 1029.23   197.9  998.66   207.8  998.19   306.8  935.92
   326.6  929.94   366.3  907.12   376.4  904.14   497.2  896.34   507.2  895.91
   517.2  897.53   547.4  903.58   587.7   908.7   607.6  918.27   687.3  944.09
   707.3  953.07   727.2  964.53   737.2  968.67   747.1  970.26   757.1  975.19
     777  998.67   846.8 1040.52   866.7  1046.5   906.6  1070.6   966.4 1098.67
#Mann= 3 , 0 , 0
       0      .1       0   497.2    .045       0   517.2      .1       0
Bank Sta=497.2,517.2
XS Rating Curve= 0 ,0
Exp/Cntr=0.3,0.1

Type RM Length L Ch R = 1 ,6024.6  ,473.3,476.6,479.9
XS GIS Cut Line= 4
     1630804.412      311310.994     1631101.346      311328.304
     1631347.682      311344.282     1631671.248      311433.496
#Sta/Elev= 30
     9.9 1083.31    79.3 1046.22    89.2 1034.63   148.7  997.02   158.6  987.12
   218.1  954.07     228  945.46     238   939.4   297.4  918.09   317.2  908.68
   327.1  905.91   415.8  894.77   425.8  894.47   435.8  894.99   455.4  899.04
   504.8   902.9   524.5  908.91   534.4  918.99   554.2  932.21   593.7  953.25
   613.4  968.29   662.8  996.35   682.5 1009.92   692.4 1021.59   702.2 1027.06
   751.6 1047.36   771.3  1058.4   810.8 1075.29   850.3 1089.98   879.9 1097.98
#Mann= 3 , 0 , 0
       0     .06       0   415.8    .045       0   435.8     .06       0
Bank Sta=415.8,435.8
XS Rating Curve= 0 ,0
Exp/Cntr=0.3,0.1

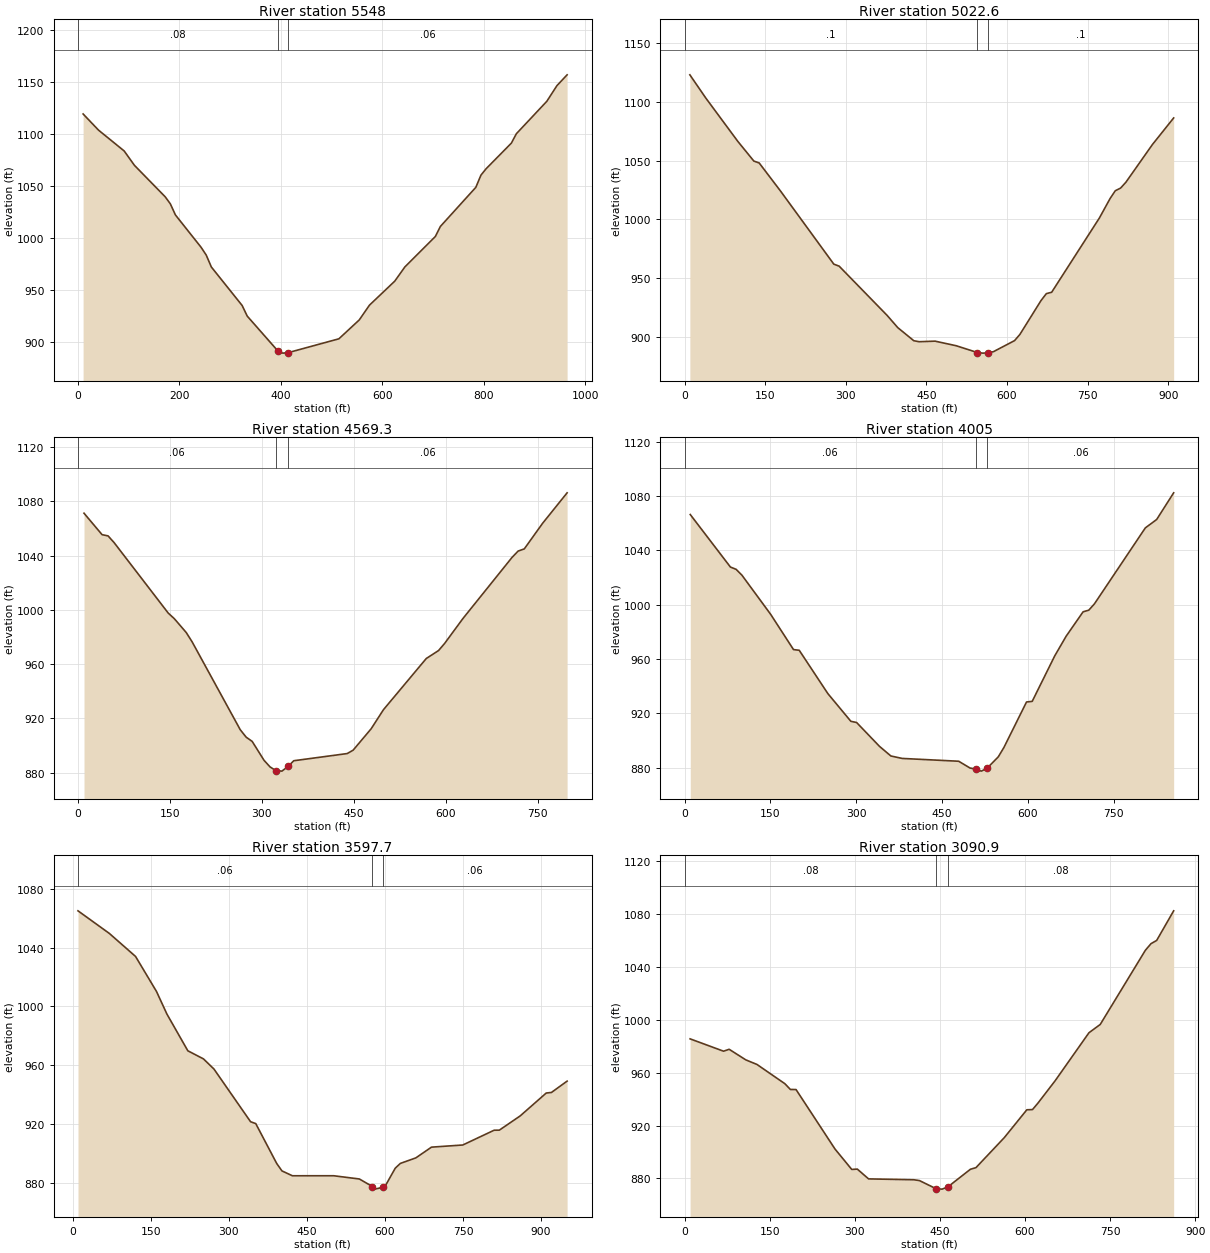
Type RM Length L Ch R = 1 ,5548    ,505.3,525.4,545.4
XS GIS Cut Line= 4
     1630672.589      311735.756     1630996.155      311734.425
     1631221.185      311786.355      1631629.97      311812.986
#Sta/Elev= 30
    10.1 1119.44    40.4 1103.94      91 1083.89   111.2 1070.11   171.9 1039.82
     182 1033.09   192.1 1022.38   242.7  991.27   252.8  983.81   262.9  972.34
   323.6  935.35   333.6  925.17   393.9  891.75   403.9  889.57   413.9  889.97
   514.3  903.33   554.5   921.5   574.5  935.63   624.5  958.78   644.4  972.42
   704.4 1001.64   714.4 1011.34   784.3 1048.94   794.3 1060.61   804.3 1066.67
   854.3 1091.41   864.2 1100.44   924.2 1131.61   944.2 1146.69   964.2 1157.06
#Mann= 3 , 0 , 0
       0     .08       0   393.9    .045       0   413.9     .06       0
Bank Sta=393.9,413.9
XS Rating Curve= 0 ,0
Exp/Cntr=0.3,0.1

Type RM Length L Ch R = 1 ,5022.6  ,459.5,453.3,447
XS GIS Cut Line= 4
      1630629.98      311775.037      1630926.47      312108.811
     1631013.464      312318.307     1631139.517      312518.926
#Sta/Elev= 30
     9.9 1122.94    39.7  1103.1    99.2  1066.3     129 1049.56   138.9 1047.96
   178.6 1024.08   277.8  961.87   287.7  960.17     377  918.27   396.8  907.87
   426.6  896.74   436.5  895.89   466.2  896.37   505.6  892.46   544.9   886.7
   554.9  886.18   564.9  886.35   574.7  887.38   614.1  896.82     624  902.05
   663.4  930.93   673.3   936.8   683.2  937.97     772 1001.15   791.8 1017.62
   801.6 1024.34   811.5 1026.61   821.4 1031.61   870.7 1063.65   910.2 1086.25
#Mann= 3 , 0 , 0
       0      .1       0   544.9    .045       0   564.9      .1       0
Bank Sta=544.9,564.9
XS Rating Curve= 0 ,0
Exp/Cntr=0.3,0.1

Type RM Length L Ch R = 1 ,4569.3  ,548.9,564.3,579.6
XS GIS Cut Line= 4
     1630397.403      312005.838     1630480.847      312236.639
     1630624.653      312407.077     1630830.599      312664.509
#Sta/Elev= 30
     9.8 1071.15    39.3 1055.34    49.1 1054.44    58.9 1049.51   147.3  997.57
   157.1  993.52   176.7  983.23   186.5   976.2   264.8  911.67   274.5  906.18
   284.2  903.12   303.6  889.15   313.3  884.34   322.7  881.64   332.7  881.21
   342.7  884.63   352.1  888.86   439.3  894.15     449  896.66   478.4  912.42
   498.4  926.43   568.3  964.15   588.3  969.99   598.3  975.28   628.3   993.7
   708.2 1038.57   718.2 1043.27   728.2 1044.85   758.1 1063.71   798.1 1086.16
#Mann= 3 , 0 , 0
       0     .06       0   322.7    .045       0   342.7     .06       0
Bank Sta=322.7,342.7
XS Rating Curve= 0 ,0
Exp/Cntr=0.3,0.1

Type RM Length L Ch R = 1 ,4005    ,392.8,407.4,422
XS GIS Cut Line= 4
     1630166.602      312135.442     1630164.827      312476.317
     1630147.073      312742.626     1630163.051      312989.406
#Sta/Elev= 30
      10 1066.43    80.2 1027.76    90.2 1026.06   100.3 1021.77   150.4  993.03
   190.5  966.96   200.5  966.45   250.6  934.51   290.8  914.13   300.8  913.26
   340.9  895.65   360.7  888.61   380.4   886.8   479.3  884.72     499  879.75
   508.8  878.93   518.8  877.44   528.8  879.52   548.5  887.96   558.4  894.91
   597.9  928.38   607.8  928.81   647.3  962.41   667.1  976.78   696.8  994.79
   706.7  995.98   716.6 1000.65   805.6  1056.6   825.4 1062.77   855.1 1082.42
#Mann= 3 , 0 , 0
       0     .06       0   508.8    .045       0   528.8     .06       0
Bank Sta=508.8,528.8
XS Rating Curve= 0 ,0
Exp/Cntr=0.3,0.1

Type RM Length L Ch R = 1 ,3597.7  ,519.3,506.8,494.4
XS GIS Cut Line= 4
     1630134.645      312131.891     1629852.358      312485.194
     1629712.102      312623.675     1629690.797      312923.716
#Sta/Elev= 30
      10 1065.17    70.3 1049.76   120.6  1034.1   160.8  1010.3   180.9  994.85
   221.1  969.83   251.2  964.29   271.3   957.4   341.7   921.5   351.7  920.21
   391.9  893.08     402     888   422.1  884.68   501.5  884.69   550.8  882.49
   575.9  877.36   580.3  875.58  596.36  876.81   600.1  877.45   619.8  889.85
   629.6   893.1   659.4  896.87   689.4  904.18   749.6  905.64   809.8  915.71
   819.8  915.75   859.9  925.45     910  941.05     920  941.44   950.1  949.15
#Mann= 3 , 0 , 0
      10     .06       0   575.9    .045       0  596.36     .06       0
Bank Sta=575.9,596.36
XS Rating Curve= 0 ,0
Exp/Cntr=0.3,0.1

Type RM Length L Ch R = 1 ,3090.9  ,643.5,638,632.5
XS GIS Cut Line= 4
     1629490.177      312076.854     1629330.392      312336.061
     1629289.558      312561.536     1629337.494      312886.433
#Sta/Elev= 30
     9.8  985.58    68.8  976.24    78.6   977.7     108  969.67   127.7   966.2
   176.8  951.65   186.6  947.27   196.5  947.23   265.2   902.2   294.7  886.75
   304.5  887.01   324.4  879.59   404.1  878.94   414.1  878.31   443.9  872.07
   453.9  871.85   463.9  873.46   503.8  886.86   513.7  888.13   563.5  910.78
   603.3   931.9   613.3  932.05   623.2  937.12   653.1  953.81   712.8   990.2
   732.7  996.49   812.3 1052.65   822.2 1057.63   832.2 1060.09   862.1 1082.48
#Mann= 3 , 0 , 0
       0     .08       0   443.9    .045       0   463.9     .08       0
Bank Sta=443.9,463.9
XS Rating Curve= 0 ,0
Exp/Cntr=0.3,0.1