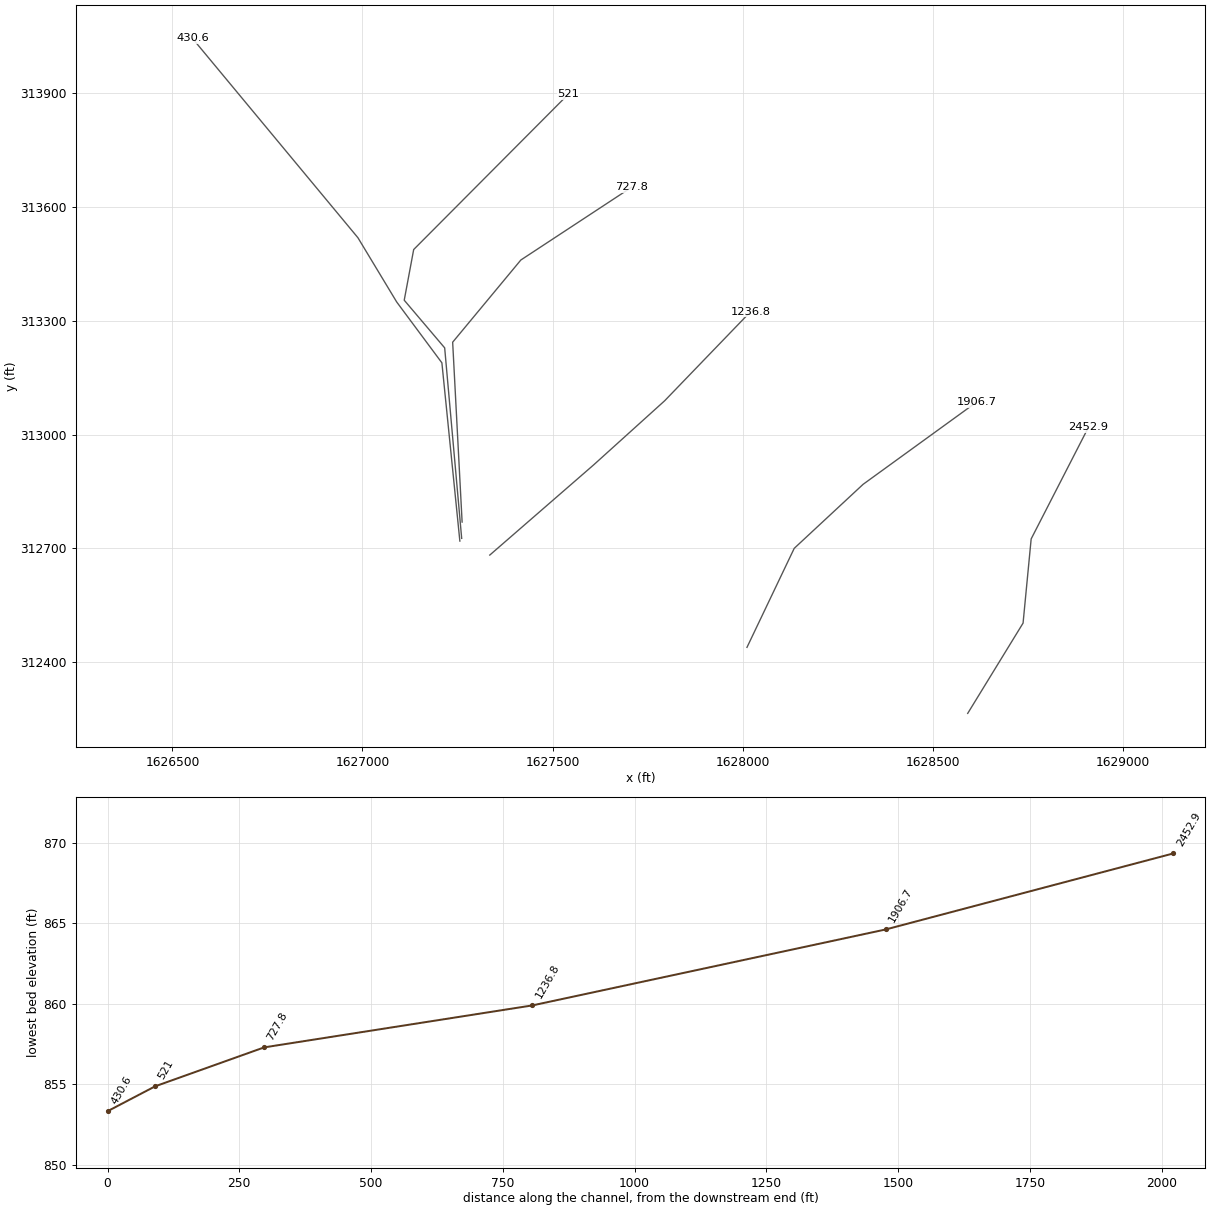
HEC-RAS study lrlfrk.prj: lrlfrk

--- lrlfrk.g01 (geometry) --- (continued)

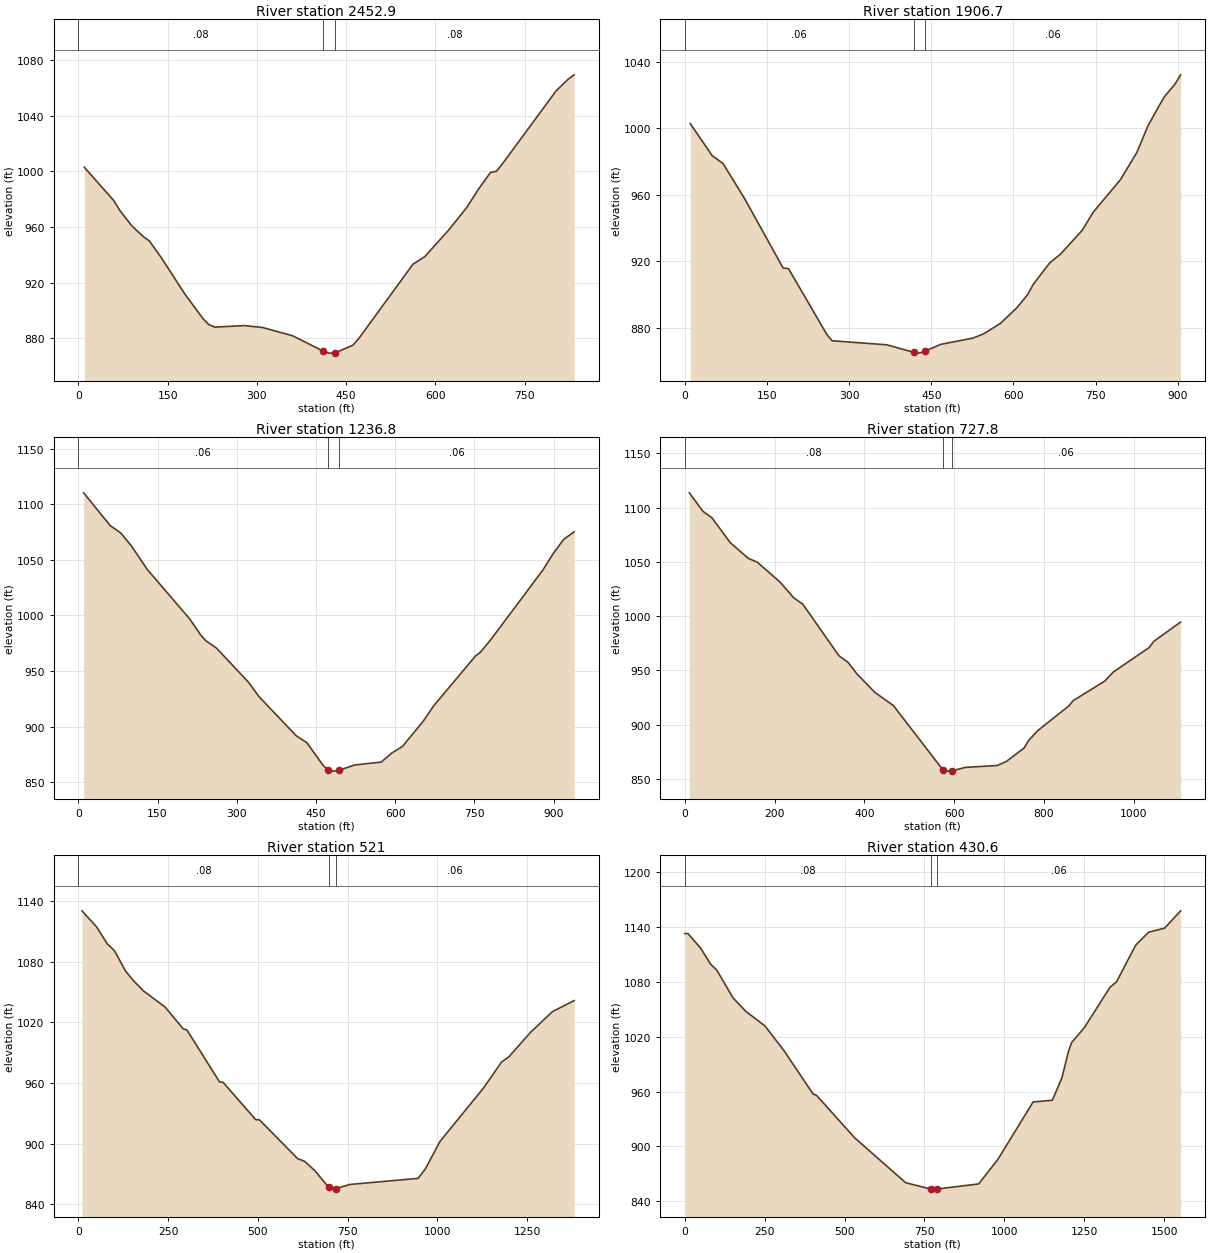
Type RM Length L Ch R = 1 ,2452.9  ,560.7,546.1,531.6
XS GIS Cut Line= 4
     1628591.829      312265.045     1628737.411      312502.948
     1628758.715      312724.872     1628909.624      313019.587
#Sta/Elev= 30
      10  1002.9    59.8  978.81    69.7  971.85    89.7  960.84   109.6  952.92
   119.5  949.85   139.5  937.88   179.3  911.58   209.2  894.27   219.1  889.91
   229.1  888.03   278.9  889.12   309.3  887.77     360  881.82   410.8  870.94
   420.8  869.35   430.8  869.41   461.3  875.04   471.5  880.02   562.1  933.19
   582.1  938.69   622.3   957.8   652.4   973.9   672.4  987.21   692.5  999.13
   702.5 1000.04   712.6  1005.4   802.9 1057.87   822.9 1066.09     833 1069.27
#Mann= 3 , 0 , 0
       0     .08       0   410.8    .045       0   430.8     .08       0
Bank Sta=410.8,430.8
XS Rating Curve= 0 ,0
Exp/Cntr=0.3,0.1

Type RM Length L Ch R = 1 ,1906.7  ,670.4,670,660.6
XS GIS Cut Line= 4
     1628011.275      312439.034     1628135.553      312700.017
     1628316.643      312868.679     1628614.909      313085.277
#Sta/Elev= 30
      10  1002.9    49.8  983.64    69.8  978.82   109.6  957.48   179.4   915.9
   189.4  915.48   259.2   875.9   269.1  872.05   368.3  869.66   417.6  865.15
   427.6  864.62   437.6  865.71   467.2   869.9   526.6  873.71   546.5  876.41
   576.4  882.61   606.3  891.97   626.2  900.01   636.2  906.09     666  918.92
     686  924.31   725.8  938.71   745.7  949.57   795.6  969.26   825.4  985.62
   845.4 1001.44   865.3 1013.29   875.3 1018.99   895.2 1026.83   905.1 1032.25
#Mann= 3 , 0 , 0
       0     .06       0   417.6    .045       0   437.6     .06       0
Bank Sta=417.6,437.6
XS Rating Curve= 0 ,0
Exp/Cntr=0.3,0.1

Type RM Length L Ch R = 1 ,1236.8  ,506.1,509,511.8
XS GIS Cut Line= 4
      1627334.85      312682.263     1627608.261      312920.165
     1627794.677      313088.828     1628020.152       313323.18
#Sta/Elev= 30
    10.1 1110.28    60.4 1080.78    80.5 1074.14   100.7 1062.36   130.9 1041.14
   211.4  996.59   231.5  982.58   241.6  977.19   261.8   970.5   322.2  939.91
   342.3  926.84   412.7  891.71   432.8  885.49     463  865.41   473.1  860.61
   483.1   859.9   493.1  860.53   523.3  865.46   573.6  868.04   593.7   876.2
   613.8  882.11   653.2  904.84   672.9   918.6   751.8   963.3   761.6  966.96
   781.3  978.32   879.9  1040.9   899.6  1055.8   919.3 1068.49     939 1075.22
#Mann= 3 , 0 , 0
       0     .06       0   473.1    .045       0   493.1     .06       0
Bank Sta=473.1,493.1
XS Rating Curve= 0 ,0
Exp/Cntr=0.3,0.1

Type RM Length L Ch R = 1 ,727.8   ,196.6,206.8,217
XS GIS Cut Line= 4
     1627262.059      312769.257     1627237.204      313243.287
     1627416.519      313459.885     1627707.683      313651.627
#Sta/Elev= 30
    10.1 1113.69    40.4 1096.67    60.6 1090.62     101 1067.91   141.4 1053.35
   161.6 1049.73   212.1 1031.49   242.4 1017.09   262.6 1011.26   343.4  963.59
   363.6   957.5   383.8  946.69   424.2  929.55   464.6  917.71   575.1   858.4
   585.1  857.29   595.1  857.51   625.3  860.76   695.6  862.48   715.7  866.03
   755.9  878.63   765.8  885.41   785.8  894.47   855.5  917.38   865.4  922.31
   935.2  940.16   955.1  948.77  1034.8  971.23  1044.7  976.85  1104.5  994.63
#Mann= 3 , 0 , 0
       0     .08       0   575.1    .045       0   595.1     .06       0
Bank Sta=575.1,595.1
XS Rating Curve= 0 ,0
Exp/Cntr=0.3,0.1

Type RM Length L Ch R = 1 ,521     ,65.9,90.4,110.7
XS GIS Cut Line= 5
     1627260.925      312726.348     1627216.192      313228.359
     1627109.816      313353.943     1627134.699      313487.527
      1627540.69      313896.137
#Sta/Elev= 30
    10.1 1130.57    50.4  1114.9    80.6 1097.84   100.8 1091.01     131 1071.17
   151.2 1062.29   181.4 1051.24   241.9 1035.13   292.3 1013.58   302.4 1012.54
   393.1  961.12   403.2  960.59   493.9  923.66     504  923.62   610.5  885.12
   629.9  882.46   658.9  873.03   697.4  856.51   707.4  854.87   717.4  855.37
   755.9  859.49   945.9  865.53   966.2   874.8  1006.6  901.98  1127.8  954.89
  1178.4   980.8  1198.6  985.93  1259.2 1010.27  1319.8 1030.65  1380.5 1041.68
#Mann= 3 , 0 , 0
       0     .08       0   697.4    .045       0   717.4     .06       0
Bank Sta=697.4,717.4
XS Rating Curve= 0 ,0
Exp/Cntr=0.3,0.1

Type RM Length L Ch R = 1 ,430.6   ,419.5,430.6,445.9
XS GIS Cut Line= 5
     1627256.129      312719.163     1627208.867      313188.927
     1627090.109      313349.135     1626988.061      313518.593
     1626552.733      314044.128
#Sta/Elev= 30
       0 1132.76      10 1132.76    50.2 1116.56    80.4 1099.57   100.5 1092.59
   150.7 1062.56   190.9 1047.73   251.1 1031.69   311.4 1004.31   401.8   957.2
   411.9  956.01     532  909.33   691.3  860.32   770.4  853.38   780.4  853.32
   790.4  853.47   919.6     859   979.8  885.79  1090.2  948.64  1150.4   950.5
  1180.5  975.33  1200.5  1003.5  1210.6 1013.56  1250.7    1030    1331 1074.21
  1351.1 1079.94  1411.3 1120.19  1451.4 1134.21  1501.6 1138.71  1551.8 1157.65
#Mann= 3 , 0 , 0
       0     .08       0   770.4    .045       0   790.4     .06       0
#XS Ineff= 2 , 0
       0     740             869       0
Permanent Ineff=
       F       F
Bank Sta=770.4,790.4
XS Rating Curve= 0 ,0
Exp/Cntr=0.3,0.1

Chan Stop Cuts=-1
Use User Specified Reach Order=0